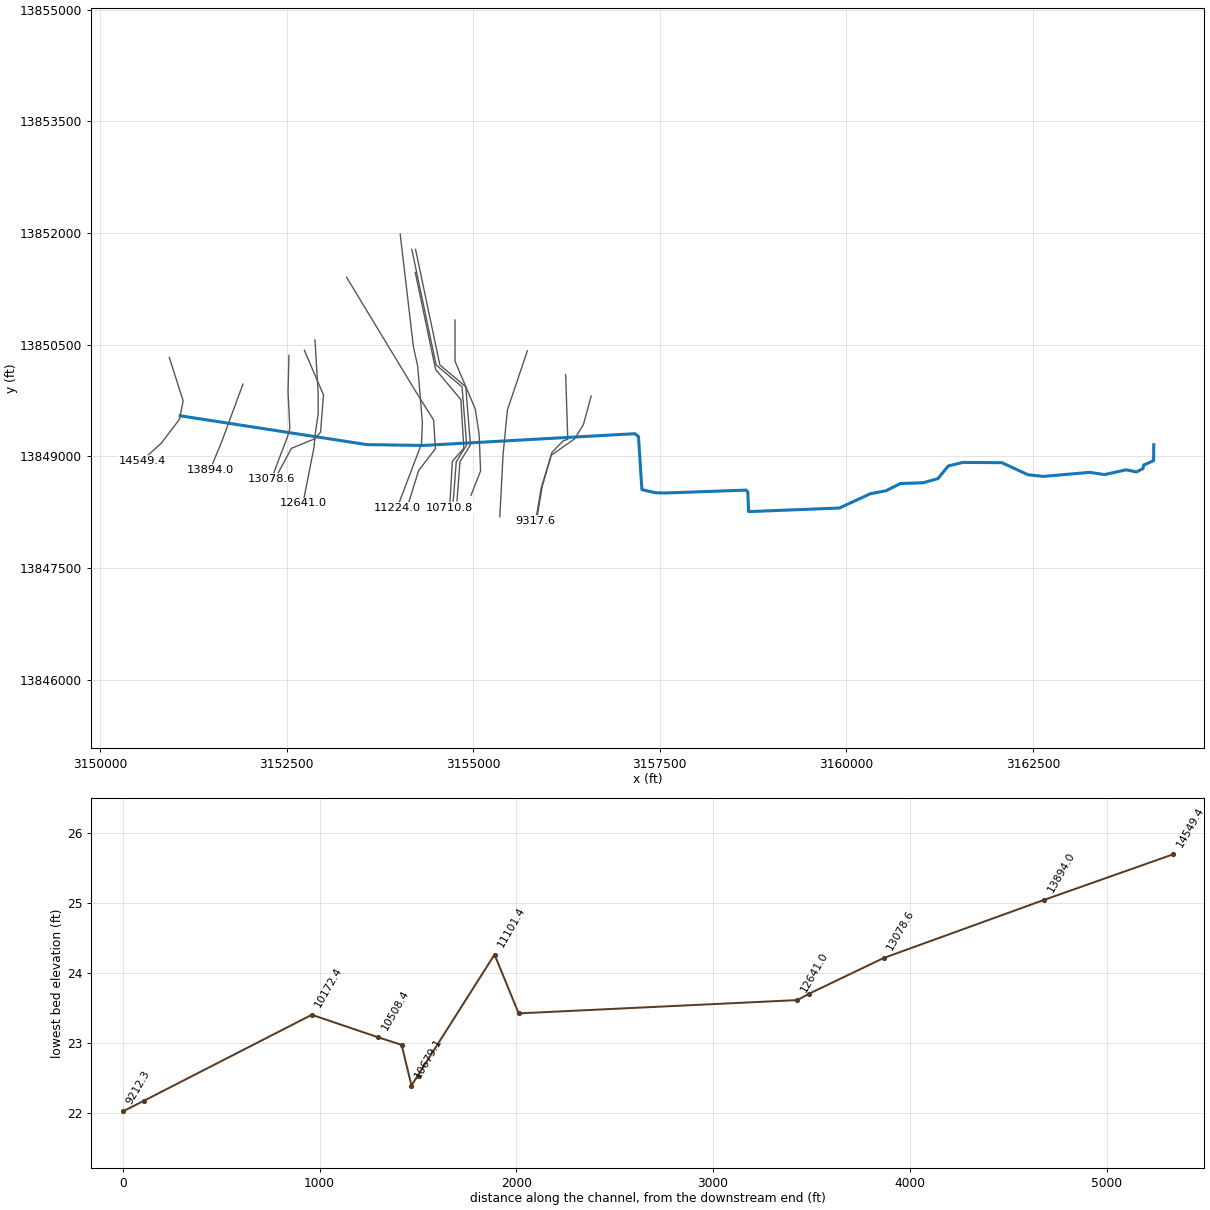
--- H103-00-00.PRJ (project) ---

Proj Title=H103-00-00
Current Plan=p03
Default Exp/Contr=.3,.1
English Units
Geom File=g01
Flow File=f01
Flow File=f03
Plan File=p01
Plan File=p03
Y Axis Title=Elevation
X Axis Title(PF)=Main Channel Distance
X Axis Title(XS)=Station
BEGIN DESCRIPTION:
Hunting Bayou Watershed
Tributary 5.22 to Hunting Bayou
HCFCD Unit H103-00-00
Flood Hazard Model
10, 2, 1, 0.2% Event
Filename H103-00-00.prj
Prepared by:  Watershed Concepts  Date: 06/04/02
Reviewed by:                      Date:
STATUS FINAL
END DESCRIPTION:
DSS Export Rating Curves= 0
DSS Export Rating Curve Sorted= 0
DSS Export Volume Flow Curves= 0
DXF OffsetX= 0
DXF OffsetY= 0
DXF ScaleX= 1
DXF ScaleY= 10

--- H103-00-00.p03 (plan) ---

Plan Title=Floodway
Version=Version 3.0.1  Mar 2001
Short Identifier=Floodway0607
Geom File=g01
Flow File=f03
Subcritical Flow
K Sum by GR= 0
Std Step Tol= 0.01
Critical Tol= 0.01
Num of Std Step Trials= 20
Max Error Tol= 0.3
Flow Tol Ratio= 0.001
Split Flow NTrial= 30
Split Flow Tol= 0.02
Split Flow Ratio= 0.02
Log Output Level= 0
Friction Slope Method= 1
Unsteady Friction Slope Method= 2
Parabolic Critical Depth
Global Vel Dist= 0 , 0 , 0
Global Log Level= 0
CheckData=True
Encroach Param=-1 ,0,0, 2
Encroach River=H103-00-00
Encroach Reach=Reach - 1
Encroach Node=14549.4
       1  4972.5  5020.5
Encroach Node=13894.0
       1  4978.5  5020.6
Encroach Node=13078.6
       1    4975    5025
Encroach Node=12699.7
       1    4960    5025
Encroach Node=12641.0
       1    4871    5050
Encroach Node=11932.5
       1    4871    5050
Encroach Node=11224.0
       1    4871    5050
Encroach Node=11101.4
       1    4960    5100
Encroach Node=10710.8
       1    4960    5080
Encroach Node=10679.1
       1    4940    5080
Encroach Node=10654.1
       1    4940    5080
Encroach Node=10629.1
       1    4940    5080
Encroach Node=10508.4
       1    4940    5070
Encroach Node=10172.4
       1    4920    5080
Encroach Node=9317.6
       1    4900    5050
Encroach Node=9212.3
       1    4860  5026.6
Encroach Node=9169.8
       1    4860  5026.6
Encroach Node=9127.3
       1    4860  5026.6
Encroach Node=9040.2
       1    4920  5026.6
Encroach Node=8492.6
       1    4960    5030
Encroach Node=7659.4
       1    4960    5030
Encroach Node=7492.2
       1    4960    5030
Encroach Node=7425.2
       1    4920    5075
Encroach Node=7399.2
       1    4920    5075
Encroach Node=7373.2
       1    4920    5075
Encroach Node=7249.8
       1    4945    5040
Encroach Node=6666.0
       1    4920    5035
Encroach Node=6245.9
       1  4982.9  5035.3
Encroach Node=6026.1
       1  4982.9  5035.3
Encroach Node=6008.6
       1  4982.9  5035.3
Encroach Node=5991.1
       1  4982.9  5035.3
Encroach Node=5936.6
       1    4968    5032
Encroach Node=5926.1
       1    4968    5032
Encroach Node=5924.1
       1    4968    5032
Encroach Node=5877.1
       1    4968    5032
Encroach Node=5830.1
       1    4968    5032
Encroach Node=5672.6
       1    4968    5032
Encroach Node=4972.0
       1    4971  5022.8
Encroach Node=4117.2
       1  4954.5  5028.6
Encroach Node=4059.0
       1  4970.9  5028.6
Encroach Node=4027.0
       1  4970.9  5028.6
Encroach Node=3995.0
       1  4970.9  5028.6
Encroach Node=3795.8
       1  4970.9  5028.6
Encroach Node=3247.8
       1 4969.16 5028.44
Encroach Node=2760.1
       1  4978.7  5026.1
Encroach Node=2708.7
       1  4978.7  5026.1
Encroach Node=2681.8
       1  4978.7  5026.1
Encroach Node=2654.9
       1  4978.7  5026.1
Encroach Node=2491.3
       1  4949.4  5026.1
Encroach Node=1881.4
       1  4956.5  5041.3
Encroach Node=973.7
       1  4971.3  5031.8
Encroach Node=935.2
       1  4971.3  5031.8
Encroach Node=886.2
       1  4971.3  5031.8
Encroach Node=837.2
       1  4971.3  5031.8
Encroach Node=757.2
       1  4971.3  5031.8
Encroach Node=442.8
       1  4955.2  5040.2
Encroach Node=431.8
       1  4955.2  5040.2
Encroach Node=420.8
       1  4955.2  5040.2
Encroach Node=331.8
       1  4975.7  5025.7
Encroach Reach=H103-00-00_0003
Encroach Node=14549.4
       1  4972.5  5020.5
Encroach Node=13894.0
       1  4978.5  5020.6
Encroach Node=13078.6
       1    4975    5025
Encroach Node=12699.7
       1    4960    5025
Encroach Node=12641.0
       1    4871    5050
Encroach Node=11932.5
       1    4871    5050
Encroach Node=11224.0
       1    4871    5050
Encroach Node=11101.4
       1    4960    5100
Encroach Node=10710.8
       1    4960    5080
Encroach Node=10679.1
       1    4940    5080
Encroach Node=10654.1
       1    4940    5080
Encroach Node=10629.1
       1    4940    5080
Encroach Node=10508.4
       1    4940    5070
Encroach Node=10172.4
       1    4920    5080
Encroach Node=9317.6
       1    4900    5050
Encroach Node=9212.3
       1    4860  5026.6
Encroach Node=9169.8
       1    4860  5026.6
Encroach Node=9127.3
       1    4860  5026.6
Encroach Node=9040.2
       1    4920  5026.6
Encroach Node=8492.6
       1    4960    5030
Encroach Node=7659.4
       1    4960    5030
Encroach Node=7492.2
       1    4960    5030
Encroach Node=7425.2
       1    4920    5075
Encroach Node=7399.2
       1    4920    5075
Encroach Node=7373.2
       1    4920    5075
Encroach Node=7249.8
       1    4945    5040
Encroach Node=6666.0
       1    4920    5035
Encroach Node=6245.9
       1  4982.9  5035.3
Encroach Node=6026.1
       1  4982.9  5035.3
Encroach Node=6008.6
       1  4982.9  5035.3
Encroach Node=5991.1
       1  4982.9  5035.3
Encroach Node=5936.6
       1    4968    5032
Encroach Node=5926.1
       1    4968    5032
Encroach Node=5924.1
       1    4968    5032
Encroach Node=5877.1
       1    4968    5032
Encroach Node=5830.1
       1    4968    5032
Encroach Node=5672.6
       1    4968    5032
Encroach Node=4972.0
       1    4971  5022.8
Encroach Node=4117.2
       1  4954.5  5028.6
Encroach Node=4059.0
       1  4970.9  5028.6
Encroach Node=4027.0
       1  4970.9  5028.6
Encroach Node=3995.0
       1  4970.9  5028.6
Encroach Node=3795.8
       1  4970.9  5028.6
Encroach Node=3247.8
       1 4969.16 5028.44
Encroach Node=2760.1
       1  4978.7  5026.1
Encroach Node=2708.7
       1  4978.7  5026.1
Encroach Node=2681.8
       1  4978.7  5026.1
Encroach Node=2654.9
       1  4978.7  5026.1
Encroach Node=2491.3
       1  4949.4  5026.1
Encroach Node=1881.4
       1  4956.5  5041.3
Encroach Node=973.7
       1  4971.3  5031.8
Encroach Node=935.2
       1  4971.3  5031.8
Encroach Node=886.2
       1  4971.3  5031.8
Encroach Node=837.2
       1  4971.3  5031.8
Encroach Node=757.2
       1  4971.3  5031.8
Encroach Node=442.8
       1  4955.2  5040.2
Encroach Node=431.8
       1  4955.2  5040.2
Encroach Node=420.8
       1  4955.2  5040.2
Encroach Node=331.8
       1  4975.7  5025.7
Computation Interval=1HOUR
Output Interval=1HOUR
Run HTab= 0
Run UNet= 0
Run PostProcess= 0
UNET Theta= 1
UNET ZTol= 0.02
UNET ZSATol= 0.1
UNET MxIter= 20
UNET MaxInSteps= 20
UNET DtIC= 0
UNET DtMin= 0
UNET MaxCRTS= 20
UNET WFStab= 2
UNET SFStab= 1
UNET WFX= 1
UNET SFX= 1
UNET Convert EG Bridges=-1
UNET Use Existing IB Tables=-1
Instantaneous Interval=1HOUR
Write IC File= 0
Write Velocity= 0
Write Detailed= 0

--- H103-00-00.p01 (plan) ---

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Plan Title=FEMA Effective June 2007
Short Identifier=FEMAeff0607
Geom File=g01
Flow File=f01
Encroach Param=-1 ,0,0, 0

--- H103-00-00.f03 (steady flow) ---

Flow Title= Floodway
Number of Profiles= 2
Profile Names=1PCT_100yr, 1PCTFloodway_100yrFW
River Rch & RM=H103-00-00,H103-00-00_0003,14549.4
     721     721
River Rch & RM=H103-00-00,H103-00-00_0003,13078.6
     852     852
River Rch & RM=H103-00-00,H103-00-00_0003,12641
     953     953
River Rch & RM=H103-00-00,H103-00-00_0003,11101.4
    1027    1027
River Rch & RM=H103-00-00,H103-00-00_0003,10679.1
    1069    1069
River Rch & RM=H103-00-00,H103-00-00_0003,10172.4
    1109    1109
River Rch & RM=H103-00-00,H103-00-00_0003,9212.3
    1202    1202
River Rch & RM=H103-00-00,H103-00-00_0003,8492.6
    1314    1314
River Rch & RM=H103-00-00,H103-00-00_0003,7425.2
    1511    1511
River Rch & RM=H103-00-00,H103-00-00_0003,6666
    1633    1633
River Rch & RM=H103-00-00,H103-00-00_0003,5936.6
    1783    1783
River Rch & RM=H103-00-00,H103-00-00_0003,4972
    1934    1934
River Rch & RM=H103-00-00,H103-00-00_0003,4059
    2106    2106
River Rch & RM=H103-00-00,H103-00-00_0003,2760.1
    2342    2342
River Rch & RM=H103-00-00,H103-00-00_0003,1881.4
    2478    2478
River Rch & RM=H103-00-00,H103-00-00_0003,442.8
    2735    2735
Boundary for River Rch & Prof#=H103-00-00,H103-00-00_0003, 1
Up Type= 0
Dn Type= 3
Dn Slope= 0.00540
Boundary for River Rch & Prof#=H103-00-00,H103-00-00_0003, 2
Up Type= 0
Dn Type= 3
Dn Slope= 0.00540

--- H103-00-00.f01 (steady flow) ---

Flow Title= FEMA Effective June 2007
Number of Profiles= 4
Profile Names=10PCT_10yr, 2PCT_50yr, 1PCT_100yr, 0.2PCT_500yr
River Rch & RM=H103-00-00,H103-00-00_0003,14549.4
     409     614     721    1033
River Rch & RM=H103-00-00,H103-00-00_0003,13078.6
     483     725     852    1220
River Rch & RM=H103-00-00,H103-00-00_0003,12641
     541     812     953    1365
River Rch & RM=H103-00-00,H103-00-00_0003,11101.4
     583     874    1027    1471
River Rch & RM=H103-00-00,H103-00-00_0003,10679.1
     607     910    1069    1531
River Rch & RM=H103-00-00,H103-00-00_0003,10172.4
     630     945    1109    1589
River Rch & RM=H103-00-00,H103-00-00_0003,9212.3
     682    1024    1202    1721
River Rch & RM=H103-00-00,H103-00-00_0003,8492.6
     743    1118    1314    1880
River Rch & RM=H103-00-00,H103-00-00_0003,7425.2
     850    1284    1511    2161
River Rch & RM=H103-00-00,H103-00-00_0003,6666
     916    1387    1633    2334
River Rch & RM=H103-00-00,H103-00-00_0003,5936.6
     998    1514    1783    2547
River Rch & RM=H103-00-00,H103-00-00_0003,4972
    1080    1641    1934    2762
River Rch & RM=H103-00-00,H103-00-00_0003,4059
    1173    1787    2106    3006
River Rch & RM=H103-00-00,H103-00-00_0003,2760.1
    1301    1986    2342    3342
River Rch & RM=H103-00-00,H103-00-00_0003,1881.4
    1375    2101    2478    3535
River Rch & RM=H103-00-00,H103-00-00_0003,442.8
    1515    2318    2735    3901
Boundary for River Rch & Prof#=H103-00-00,H103-00-00_0003, 1
Up Type= 0
Dn Type= 3
Dn Slope= 0.00540
Boundary for River Rch & Prof#=H103-00-00,H103-00-00_0003, 2
Up Type= 0
Dn Type= 3
Dn Slope= 0.00540
Boundary for River Rch & Prof#=H103-00-00,H103-00-00_0003, 3
Up Type= 0
Dn Type= 3
Dn Slope= 0.00540
Boundary for River Rch & Prof#=H103-00-00,H103-00-00_0003, 4
Up Type= 0
Dn Type= 3
Dn Slope= 0.00540

--- H103-00-00.g01 (geometry) ---

Geom Title=H103-00-00 June 2007

River Reach=H103-00-00,H103-00-00_0003
Reach XY= 30
      3151074.79     13849545.90      3153576.81     13849158.46
      3154335.23     13849147.63      3157168.16     13849305.36
      3157214.55     13849266.71      3157260.75        13848554
      3157438.77     13848512.87      3157570.21        13848509
       3158656.5     13848547.66      3158679.75        13848523
         3158690        13848259      3159905.76     13848307.08
      3160322.88     13848499.23      3160533.78     13848539.85
      3160724.37      13848636.7         3161029     13848646.08
      3161227.41     13848702.32       3161365.5        13848872
      3161561.72     13848919.47      3162084.25        13848916
      3162433.44     13848753.87         3162638        13848732
      3163261.11     13848786.26      3163459.47     13848756.19
      3163748.74     13848820.11      3163887.01     13848791.67
      3163973.38      13848836.1      3163983.75        13848884
       3164116.7     13848943.46      3164118.62     13849157.72

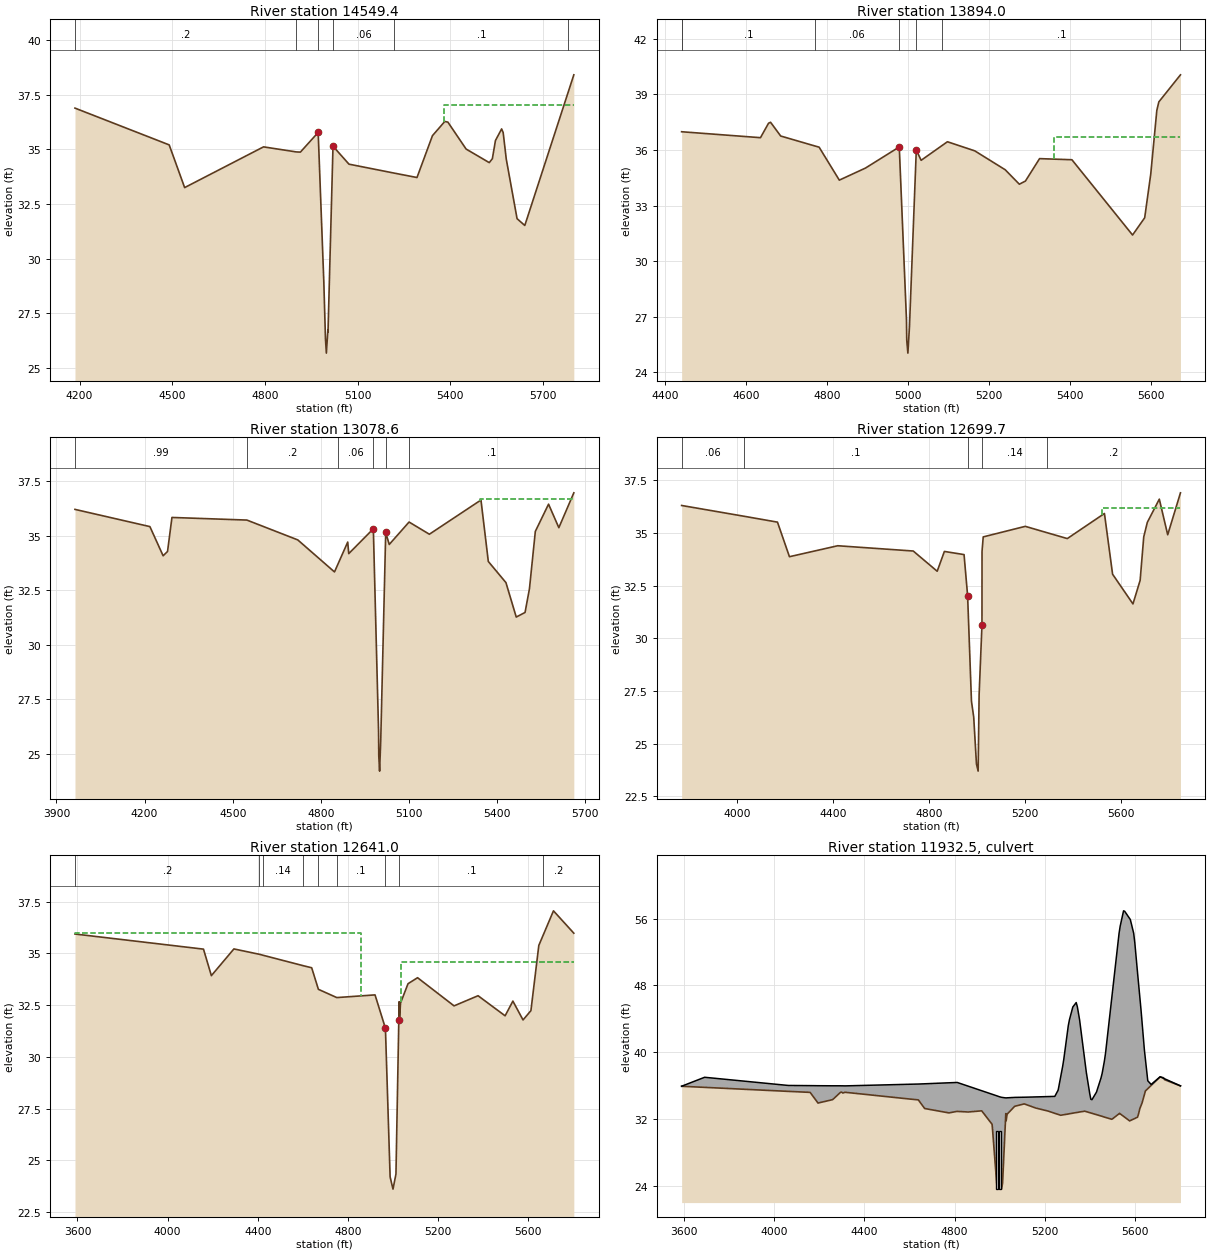
Type RM Length L Ch R = 1 ,14549.4,682.6,655.4,654.7
XS GIS Cut Line= 6
      3150928.63     13850327.95      3151114.24     13849746.48
      3151088.27     13849614.63      3151065.60     13849499.38
      3150821.23     13849177.71      3150562.82     13848943.61
BEGIN DESCRIPTION:
Cross Section 14549.4
END DESCRIPTION:
#Sta/Elev= 30
  4185.2   36.88  4490.2    35.2  4540.2   33.25  4795.6   35.11  4901.1   34.88
  4914.9   34.87  4972.5   35.77  4990.8   28.93  4996.1   26.34    4999   25.69
  5003.9   26.74  5004.3   26.65  5020.5   35.14  5072.2   34.32  5219.1   33.91
  5292.4   33.71  5342.4   35.62  5382.4   36.27  5392.4   36.24  5451.4   35.01
  5526.4   34.39  5536.4   34.57  5546.4    35.4  5566.4   35.93  5571.4   35.76
  5581.4   34.55  5616.4   31.83  5641.4   31.52  5782.8   37.65  5800.1    38.4
#Mann= 6 , 1 , 0
 4185.20     0.2       0  4901.1    0.06       0  4972.5    0.04       0
  5020.5    0.06       0  5219.1     0.1       0  5782.8     0.2       0
#XS Ineff= 2 , 0
       0                    5380       0      37
Bank Sta=4972.50,5020.50
Exp/Cntr=0.3,0.1

Type RM Length L Ch R = 1 ,13894.0,704.5,815.4,816.5
XS GIS Cut Line= 3
      3151915.69     13849971.19      3151639.04     13849220.27
      3151474.87     13848818.97
BEGIN DESCRIPTION:
Cross Section 13894.0
END DESCRIPTION:
#Sta/Elev= 30
  4440.2   36.98  4635.2   36.66  4655.2   37.44  4660.2   37.49  4685.2   36.75
  4770.2   36.21  4780.2   36.15  4830.2   34.37  4894.8   35.02  4978.5   36.16
  4996.3   26.85    4997   25.74  4999.8   25.04  5003.7   26.46  5020.6   35.99
  5032.6   35.44  5085.2   36.25  5097.6   36.44  5165.2   35.95  5240.5   34.93
  5275.5   34.15  5290.5   34.32  5325.5   35.53  5405.5   35.47  5555.5   31.41
  5585.5   32.34  5600.5    34.7  5615.5   38.13  5620.5   38.59    5674   40.05
#Mann= 7 , 1 , 0
 4440.20     0.2       0  4440.2     0.1       0  4770.2    0.06       0
  4978.5    0.04       0  5020.6    0.06       0  5085.2     0.1       0
    5674     0.2       0
#XS Ineff= 2 , 0
       0                    5360       0    36.7
Bank Sta=4978.50,5020.60
Exp/Cntr=0.3,0.1

Type RM Length L Ch R = 1 ,13078.6,450.8,378.9,287.8
XS GIS Cut Line= 6
      3152531.50     13850355.57      3152519.57     13849866.42
      3152543.44     13849377.26      3152515.60     13849273.86
      3152424.13     13849035.25      3152300.85     13848701.19
BEGIN DESCRIPTION:
Cross Section 13078.6
Located At: 1ST XS US E LOOP 610
END DESCRIPTION:
#Sta/Elev= 30
  3963.1   36.22  4218.1   35.43  4263.1   34.09  4278.1   34.29  4293.1   35.85
  4548.1   35.73  4721.3   34.82  4846.3   33.35  4859.1   33.74  4891.3   34.72
  4894.8   34.19  4978.5   35.33  4996.3   26.02    4997   24.91  4999.8   24.21
  5003.7   25.63  5020.6   35.16  5032.6   34.61  5100.1   35.64  5169.2   35.08
  5344.8   36.65  5369.8   33.83  5429.8   32.86  5464.8   31.28  5494.8   31.49
  5509.8   32.58  5529.8   35.21  5574.8   36.46  5609.8   35.38  5660.8   36.98
#Mann= 6 , 1 , 0
 3963.10    0.99       0  4548.1     0.2       0  4859.1    0.06       0
  4978.5    0.04       0  5020.6    0.06       0  5100.1     0.1       0
#XS Ineff= 2 , 0
       0                    5340       0    36.7
Bank Sta=4978.50,5020.60
Exp/Cntr=0.3,0.1

Type RM Length L Ch R = 1 ,12699.7,205.4,58.7,57
XS GIS Cut Line= 6
      3152738.26     13850425.06      3152994.47     13849825.93
      3152955.05     13849325.35      3152877.58     13849236.82
      3152564.84     13849108.49      3152344.10     13848698.64
BEGIN DESCRIPTION:
Cross Section 12699.7 - Interpolated
END DESCRIPTION:
#Sta/Elev= 30
  3767.6    36.3  4027.4   35.79  4167.6   35.51  4217.6   33.87  4419.2   34.39
  4734.2   34.14  4834.2   33.18  4864.2   34.12  4946.3   33.97 4961.15   32.02
 4977.25   27.01 4986.55   26.27 4998.05   24.04 5005.05    23.7 5009.15   27.32
 5021.05   30.63  5021.3   34.12  5026.3   34.81  5201.9   35.31  5292.3   35.01
  5377.2   34.73  5532.2   35.92  5566.2   33.04  5651.2   31.63  5681.2   32.75
  5696.2   34.81  5711.2    35.5  5761.2    36.6  5796.2   34.91  5849.5    36.9
#Mann= 5 , 1 , 0
 3767.60    0.06       0  4027.4     0.1       0 4961.15    0.04       0
 5021.05    0.14       0  5292.3     0.2       0
#XS Ineff= 2 , 0
       0                    5522       0    36.2
Bank Sta=4961.15,5021.05
Exp/Cntr=0.5,0.3

Type RM Length L Ch R = 1 ,12641.0,1417,1417,1417
XS GIS Cut Line= 6
      3152880.21     13850564.60      3152923.31     13849844.60
      3152923.31     13849573.56      3152886.82     13849323.36
      3152865.97     13849114.86      3152719.47     13848371.12
BEGIN DESCRIPTION:
Upstream Section of Bridge/Culvert/Weir
END DESCRIPTION:
#Sta/Elev= 30
  3589.1   35.93  4159.1    35.2  4194.1   33.92  4294.1   35.21  4407.4   34.95
  4424.9    34.9  4601.6    34.4  4639.1    34.3  4668.8   33.26  4750.4   32.86
  4920.1   32.99  4966.2   31.38    4987    24.2  4999.8   23.61  5012.9   24.34
  5027.1   32.66  5028.6    31.8  5033.1   32.59  5066.4   33.53  5108.8   33.82
  5270.6   32.46  5377.1   32.95  5497.1   31.98  5531.6   32.69  5576.6   31.78
  5611.6   32.23  5646.6   35.38  5667.3   35.91  5711.6   37.05  5801.9   35.97
#Mann= 9 , 1 , 0
 3589.10     0.2       0  4407.4     0.1       0  4424.9    0.14       0
  4601.6     0.1       0  4668.8    0.04       0  4750.4     0.1       0
  4966.2    0.04       0  5028.6     0.1       0  5667.3     0.2       0
#XS Ineff= 2 , 0
       0    4857   35.98    5035       0    34.6
Bank Sta=4966.20,5028.60
Exp/Cntr=0.5,0.3

Type RM Length L Ch R = 2 ,11932.5,,,
BEGIN DESCRIPTION:
INTERSTATE ROUTE 610
Structure ID: H03-9
END DESCRIPTION:
Bridge Culvert--1,0,-1,-1, 0
Deck Dist Width WeirC Skew NumUp NumDn MinLoCord MaxHiCord MaxSubmerge Is_Ogee
10,1397,3,, 60, 60,,,0.95,0,1,1,,
  3589.1  3691.1  4062.3  4159.1  4194.1  4259.1  4294.1  4314.1  4639.1  4667.1
  4775.1  4811.6  4920.1  4966.2    4987  4992.2  4999.8  5008.1  5012.9  5027.1
  5028.6  5033.1  5066.4  5108.8  5244.4  5259.4  5279.4  5284.4  5304.4  5309.4
  5324.4  5339.4  5344.4  5354.4  5384.4  5399.4  5404.4  5409.4  5429.4  5449.4
  5454.4  5464.4  5469.4  5497.1  5529.4  5534.4  5549.4  5554.4  5579.4  5594.4
  5599.4  5611.6  5621.6  5626.9  5641.9  5646.6  5656.9  5671.9  5711.6  5801.9
   35.93      37   36.02      36   35.99   35.98   35.98   35.97   36.19   36.22
   36.34   36.38   35.39   34.97   34.78   34.73   34.66    34.6   34.58   34.53
   34.53   34.54   34.59   34.61   34.71   35.47   38.33   39.18   43.21    43.9
   45.42   45.95   45.46   43.89   37.57   35.05   34.36   34.32   35.23   36.92
   37.46   38.95   39.87    46.5   54.23    55.1   56.94   56.89    55.9   54.25
   53.11   49.49   46.61   45.08   40.27   39.11   36.58   36.14   37.06   35.97
   35.92   35.79   35.31   35.19   33.91   34.32    35.2    35.2   34.29   33.26
   32.73   32.91   32.98   31.37   24.19   23.62    23.6   23.61   24.33   32.65
   31.79   32.58   33.52   33.81   32.68   32.55   32.49   32.51    32.6   32.63
    32.7   32.77   32.79   32.84   32.88   32.76   32.72   32.68   32.52   32.36
   32.32   32.23   32.19   31.97   32.63   32.62   32.32   32.22   31.81      32
   32.06   32.22   33.24    33.6   34.92   35.37   35.63   36.02   37.04   35.96
  3589.1  3691.1  4062.3  4159.1  4194.1  4259.1  4294.1  4314.1  4639.1  4667.1
  4775.1  4811.6  4920.1  4966.2    4987  4992.2  4999.8  5008.1  5012.9  5027.1
  5028.6  5033.1  5066.4  5108.8  5244.4  5259.4  5279.4  5284.4  5304.4  5309.4
  5324.4  5339.4  5344.4  5354.4  5384.4  5399.4  5404.4  5409.4  5429.4  5449.4
  5454.4  5464.4  5469.4  5497.1  5529.4  5534.4  5549.4  5554.4  5579.4  5594.4
  5599.4  5611.6  5621.6  5626.9  5641.9  5646.6  5656.9  5671.9  5711.6  5801.9
   35.93      37   36.02      36   35.99   35.98   35.98   35.97   36.19   36.22
   36.34   36.38   35.39   34.97   34.78   34.73   34.66    34.6   34.58   34.53
   34.53   34.54   34.59   34.61   34.71   35.47   38.33   39.18   43.21    43.9
   45.42   45.95   45.46   43.89   37.57   35.05   34.36   34.32   35.23   36.92
   37.46   38.95   39.87    46.5   54.23    55.1   56.94   56.89    55.9   54.25
   53.11   49.49   46.61   45.08   40.27   39.11   36.58   36.14   37.06   35.97
   35.57   35.44   34.96   34.84   33.56   33.97   34.85   34.85   33.94   32.91
   32.38   32.56   32.63   31.02   23.84   23.27   23.25   23.26   23.98    32.3
   31.44   32.23   33.17   33.46   32.33    32.2   32.14   32.16   32.25   32.28
   32.35   32.42   32.44   32.49   32.53   32.41   32.37   32.33   32.17   32.01
   31.97   31.88   31.84   31.62   32.28   32.27   31.97   31.87   31.46   31.65
   31.71   31.87   32.89   33.25   34.57   35.02   35.28   35.67   36.69   35.61
BR Coef= 1 , 0 , 0 ,1.25, 0 ,,,0.8,-1,2,0,
Wspro=,,,, 1 ,,,, 0 ,,,, 0 ,,,,-1 ,-1 ,-1 , 0 , 0 , 0 , 0 , 0
Culvert=2,7.0,10.0,1397.0,0.015,0.4,1.0,8,1,23.60,4987.20,22.56,4987.20,Culvert #1  ,0,10
Culvert=2,7.0,10.0,1397.0,0.015,0.4,1.0,8,1,23.60,5000.40,22.55,5000.40,Culvert #2  ,0,10
BC Design=,, 0 ,, 0 ,,,,,,
BR U #Sta/Elev= 95
  3589.1   35.92  3691.1   35.79  4062.3   35.31  4159.1   35.19  4194.1   33.91
  4259.1   34.32  4294.1    35.2  4299.1   35.22  4304.1   35.11  4314.1    35.2
  4407.4   34.94  4424.9   34.89  4427.8   34.88  4601.6   34.39  4639.1   34.29
  4667.1   33.26  4668.8   33.25  4750.4   32.85  4775.1   32.73  4810.1   32.91
  4811.6   32.91  4860.6   32.84  4920.1   32.98  4966.2   31.37  4968.6   30.63
    4987   24.19  4992.2   23.62  4996.6   23.61  4999.8    23.6  5001.6    23.6
  5008.1   23.61  5012.9   24.33  5023.3   30.42  5027.1   32.65  5028.6   31.79
  5033.1   32.58    5057   33.25  5066.4   33.52  5108.8   33.81  5117.3   33.73
  5159.4   33.32  5177.2    33.2  5214.7   32.95  5233.5   32.78  5244.4   32.68
  5259.4   32.55  5270.6   32.45  5270.8   32.45  5279.4   32.49  5284.4   32.51
  5304.4    32.6  5309.4   32.63  5324.4    32.7  5339.4   32.77  5344.4   32.79
  5349.4   32.81  5354.4   32.84  5364.4   32.88  5369.4    32.9  5377.1   32.94
  5384.4   32.88  5399.4   32.76  5404.4   32.72  5409.4   32.68  5429.4   32.52
  5449.4   32.36  5454.4   32.32  5464.4   32.23  5469.4   32.19  5497.1   31.97
  5502.1   32.05  5529.4   32.63  5531.6   32.68  5534.4   32.62  5549.4   32.32
  5554.4   32.22  5576.6   31.77  5579.4   31.81  5594.4      32  5599.4   32.06
  5601.9    32.1  5611.6   32.22  5616.6   32.67  5621.6   33.24  5626.9    33.6
  5631.6   33.92  5641.9   34.92  5646.6   35.37  5656.9   35.63  5667.3    35.9
  5671.9   36.02  5711.6   37.04  5726.6   36.94  5731.6   36.71  5801.9   35.96
BR U #Mann= 9
 3589.10     0.2  4407.4     0.1  4424.9    0.14  4601.6     0.1  4668.8    0.04
  4750.4     0.1  4966.2    0.04  5028.6     0.1  5667.3     0.2
BR U Banks=4966.20,5028.60
BR D #Sta/Elev= 95
  3589.1   35.57  3691.1   35.44  4062.3   34.96  4159.1   34.84  4194.1   33.56
  4259.1   33.97  4294.1   34.85  4299.1   34.87  4304.1   34.76  4314.1   34.85
  4407.4   34.59  4424.9   34.54  4427.8   34.53  4601.6   34.04  4639.1   33.94
  4667.1   32.91  4668.8    32.9  4750.4    32.5  4775.1   32.38  4810.1   32.56
  4811.6   32.56  4860.6   32.49  4920.1   32.63  4966.2   31.02  4968.6   30.28
    4987   23.84  4992.2   23.27  4996.6   23.26  4999.8   23.25  5001.6   23.25
  5008.1   23.26  5012.9   23.98  5023.3   30.07  5027.1    32.3  5028.6   31.44
  5033.1   32.23    5057    32.9  5066.4   33.17  5108.8   33.46  5117.3   33.38
  5159.4   32.97  5177.2   32.85  5214.7    32.6  5233.5   32.43  5244.4   32.33
  5259.4    32.2  5270.6    32.1  5270.8    32.1  5279.4   32.14  5284.4   32.16
  5304.4   32.25  5309.4   32.28  5324.4   32.35  5339.4   32.42  5344.4   32.44
  5349.4   32.46  5354.4   32.49  5364.4   32.53  5369.4   32.55  5377.1   32.59
  5384.4   32.53  5399.4   32.41  5404.4   32.37  5409.4   32.33  5429.4   32.17
  5449.4   32.01  5454.4   31.97  5464.4   31.88  5469.4   31.84  5497.1   31.62
  5502.1    31.7  5529.4   32.28  5531.6   32.33  5534.4   32.27  5549.4   31.97
  5554.4   31.87  5576.6   31.42  5579.4   31.46  5594.4   31.65  5599.4   31.71
  5601.9   31.75  5611.6   31.87  5616.6   32.32  5621.6   32.89  5626.9   33.25
  5631.6   33.57  5641.9   34.57  5646.6   35.02  5656.9   35.28  5667.3   35.55
  5671.9   35.67  5711.6   36.69  5726.6   36.59  5731.6   36.36  5801.9   35.61
BR D #Mann= 9
 3589.10     0.2  4407.4     0.1  4424.9    0.14  4601.6     0.1  4668.8    0.04
  4750.4     0.1  4966.2    0.04  5028.6     0.1  5667.3     0.2
BR D Banks=4966.20,5028.60

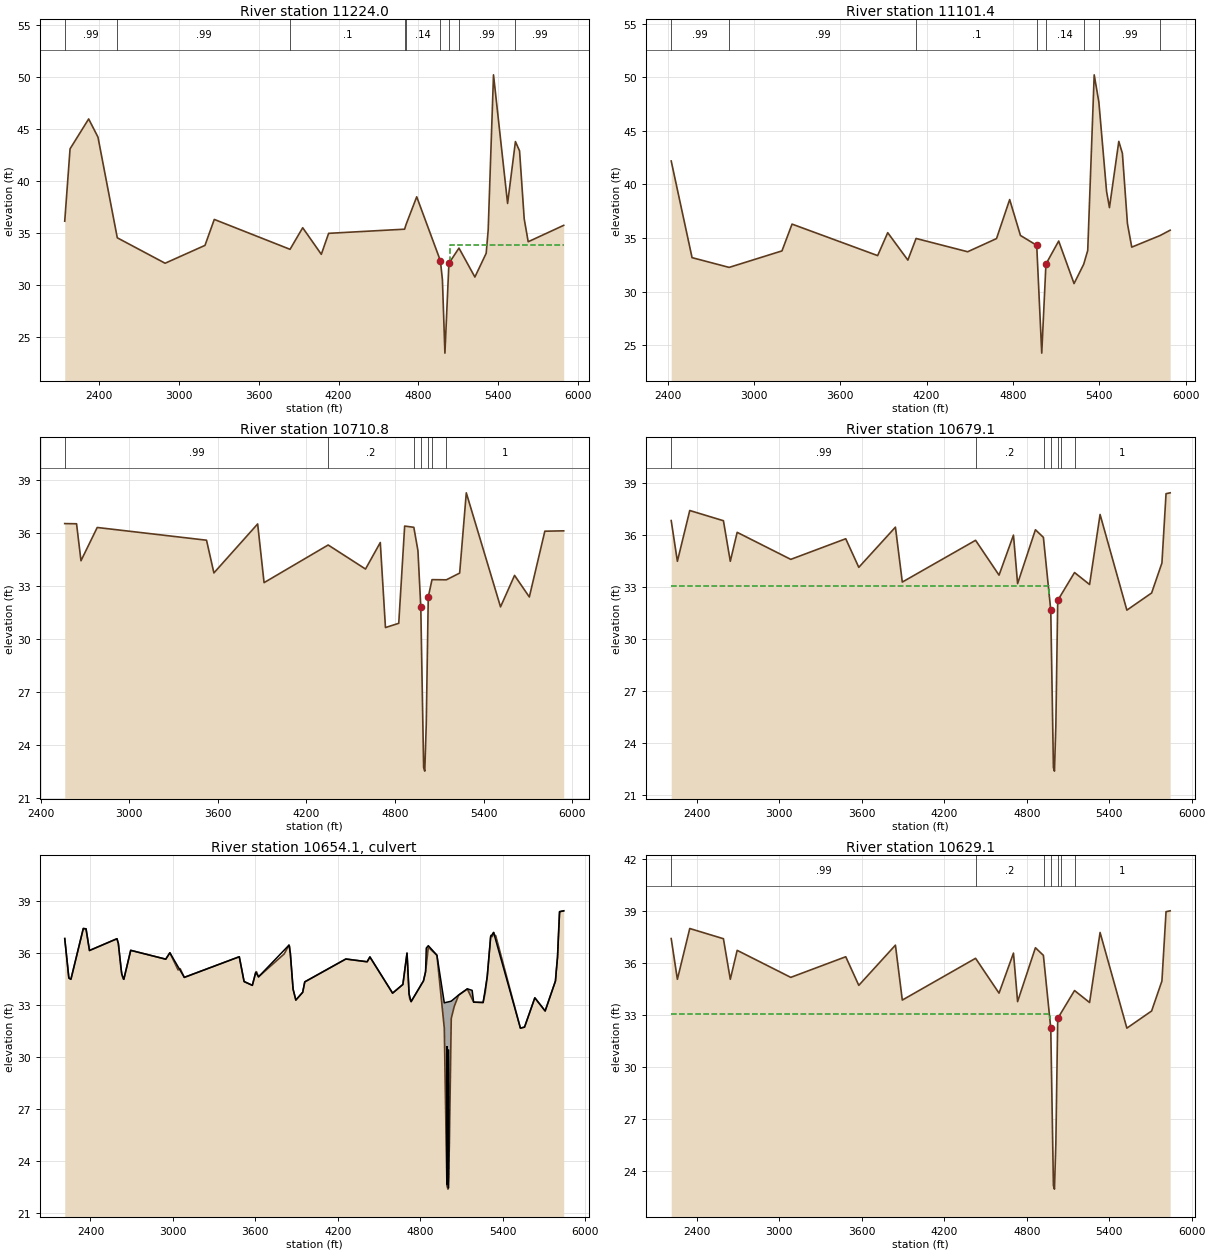
Type RM Length L Ch R = 1 ,11224.0,122.6,122.6,122.6
XS GIS Cut Line= 6
      3154021.98     13851986.39      3154198.31     13850478.22
      3154256.80     13850210.83      3154319.47     13849452.52
      3154306.94     13849168.41      3153982.83     13848313.78
BEGIN DESCRIPTION:
Downstream Section of Bridge/Culvert/Weir
Located At: B section to Loop 610
END DESCRIPTION:
#Sta/Elev= 30
  2140.4   36.13  2180.4    43.1  2320.4   45.98  2390.4   44.23  2535.7   34.53
  2895.4   32.08  3195.3    33.8  3265.3    36.3  3835.1   33.42  3930.3    35.5
  4070.3   32.94  4125.3   34.96  4696.7   35.36  4707.7   35.81  4787.9   38.48
  4965.9   32.32  4981.1   30.51    5000   23.42    5030   32.07  5105.6   33.54
  5225.4   30.75  5310.4   33.04  5325.4   35.28  5365.4   50.23  5471.4   37.84
  5530.3    43.8  5561.4    42.9  5596.4   36.35  5626.4   34.15  5893.4   35.73
#Mann= 9 , 1 , 0
 2140.40    0.99       0  2535.7    0.99       0  3835.1     0.1       0
  4696.7    0.14       0  4707.7    0.14       0  4965.9    0.04       0
    5030    0.99       0  5105.6    0.99       0  5530.3    0.99       0
#XS Ineff= 2 , 0
       0    4835   35.95    5035       0    33.8
Bank Sta=4965.90,5030.00
Exp/Cntr=0.5,0.3

Type RM Length L Ch R = 1 ,11101.4,389,390.6,399.2
XS GIS Cut Line= 6
      3153303.86     13851405.16      3154258.24     13849825.56
      3154468.99     13849490.81      3154495.01     13849104.80
      3154268.35     13848808.84      3154130.45     13848362.70
BEGIN DESCRIPTION:
Cross Section 11101.4
Located At: 1ST XS DS E LOOP 610
END DESCRIPTION:
#Sta/Elev= 30
  2425.4   42.19  2570.4   33.17    2828   32.26  3195.3    33.8  3265.3    36.3
  3860.3   33.36  3930.3    35.5  4070.3   32.94  4127.4   34.96  4485.9   33.72
  4686.5   34.95  4777.9   38.59  4852.9   35.24  4965.9   34.32  5000.8   24.26
    5030   32.57  5118.6   34.72  5225.4   30.75  5292.3   32.55  5320.4   33.84
  5365.4   50.23  5397.9   47.68  5451.4   39.35  5471.4   37.84  5536.4   44.02
  5561.4    42.9  5596.4   36.35  5626.4   34.15  5822.6   35.23  5893.4   35.73
#Mann= 8 , 1 , 0
 2425.40    0.99       0    2828    0.99       0  4127.4     0.1       0
  4965.9    0.04       0    5030    0.14       0  5292.3    0.99       0
  5397.9    0.99       0  5822.6    0.99       0
Bank Sta=4965.90,5030.00
Exp/Cntr=0.3,0.1

Type RM Length L Ch R = 1 ,10710.8,31,31.7,65.9
XS GIS Cut Line= 6
      3154224.24     13851469.58      3154496.21     13850168.85
      3154835.19     13849762.87      3154874.61     13849108.56
      3154720.88     13848935.13      3154685.41     13848308.42
BEGIN DESCRIPTION:
Cross Section 10710.8 - Interpolated
END DESCRIPTION:
#Sta/Elev= 30
  2564.1   36.53  2644.1   36.52  2674.1   34.43  2784.1   36.31  3524.1   35.59
  3574.1   33.74  3870.3   36.51  3913.7   33.19  4347.7   35.32  4600.6   33.96
  4700.6   35.46  4735.6   30.65  4825.6   30.89  4865.6   36.39  4927.7   36.32
  4955.5      35  4974.8   31.82  4994.1   22.73  5001.7   22.53  5011.8   25.18
  5025.4   32.38  5050.8   33.36  5147.7   33.35  5237.9   33.73  5282.9   38.27
  5514.7   31.82  5609.7    33.6  5709.7   32.38  5814.7    36.1  5942.4   36.12
#Mann= 7 , 1 , 0
 2564.10    0.99       0  4347.7     0.2       0  4927.7     0.1       0
  4974.8    0.04       0  5025.4    0.14       0  5050.8     0.2       0
  5147.7       1       0
Bank Sta=4974.80,5025.40
Exp/Cntr=0.5,0.3

Type RM Length L Ch R = 1 ,10679.1,50,50,50
XS GIS Cut Line= 6
      3154177.84     13851780.31      3154503.43     13850227.69
      3154850.76     13849934.76      3154913.12     13849154.44
      3154773.34     13848928.35      3154733.16     13848402.37
BEGIN DESCRIPTION:
Upstream Section of Bridge/Culvert/Weir
END DESCRIPTION:
#Sta/Elev= 30
  2212.9   36.85  2257.9    34.5  2347.9   37.43  2592.9   36.84  2642.9    34.5
  2692.9   36.17  3082.9   34.61  3482.9    35.8  3577.9   34.15  3844.5   36.47
  3894.5    33.3  4427.7   35.71  4598.4    33.7  4703.4   36.01  4733.4   33.21
  4863.1   36.32  4921.2   35.88  4974.8   31.68  4994.1   22.59  5001.7   22.39
  5011.8   25.04  5025.4   32.24  5147.7   33.85  5257.2   33.16  5333.6    37.2
  5528.6   31.68  5708.6   32.67  5783.6    34.4  5813.6    38.4  5843.6   38.45
#Mann= 7 , 1 , 0
 2212.90    0.99       0  4427.7     0.2       0  4927.7     0.1       0
  4974.8    0.04       0  5025.4    0.11       0  5050.8     0.1       0
  5147.7       1       0
#XS Ineff= 2 , 0
       0  4964.8   33.09  5035.4       0   31.64
Bank Sta=4974.80,5025.40
Exp/Cntr=0.5,0.3

Type RM Length L Ch R = 2 ,10654.1,,,
BEGIN DESCRIPTION:
ACCESS ROAD
Structure ID: H03-8
END DESCRIPTION:
Bridge Culvert--1,0,-1,-1, 0
Deck Dist Width WeirC Skew NumUp NumDn MinLoCord MaxHiCord MaxSubmerge Is_Ogee
10,30,3,, 60, 60,,,0.95,0,1,1,,
  2212.9  2242.9  2257.9  2347.9  2367.9  2392.9  2592.9  2602.9  2627.9  2642.9
  2692.9  2947.9  2977.9  3082.9  3482.9  3517.9  3577.9  3602.9  3622.9  3844.5
  3854.5  3874.5  3894.5  3944.5  3959.5  4258.4  4413.4  4433.4  4598.4  4673.4
  4703.4  4718.4  4733.4  4823.4  4838.4  4843.5  4858.4  4921.2  4974.8  4994.1
  5001.7  5005.9  5011.8  5025.4  5078.7  5142.4  5177.4  5188.3  5257.2  5287.2
  5312.2  5333.6  5528.6  5558.6  5633.6  5708.6  5783.6  5798.6  5813.6  5843.6
   36.81   34.53   34.46   37.39   37.37   36.12    36.8   36.53   34.76   34.46
   36.13   35.62   35.99   34.57   35.76   34.33   34.11   34.86    34.6   36.43
   35.95   33.89   33.26   33.71   34.31   35.63   35.47   35.75   33.66   34.16
   35.97   33.62   33.17   34.37   34.89   36.26    36.4   35.85    33.1   33.14
   33.15   33.16   33.17    33.2   33.55   33.91   33.82   33.14   33.12   34.61
   36.92   37.16   31.64    31.7   33.39   32.63   34.36   35.73   38.36   38.41
   36.81   34.53   34.46   37.39   37.37   36.12    36.8   36.53   34.76   34.46
   36.13   35.62   35.99   34.57   35.76   34.33   34.11   34.86    34.6   36.43
   35.95   33.89   33.26   33.71   34.31   35.63   35.47   35.75   33.66   34.16
   35.97   33.62   33.17   34.37   34.89   35.25   36.31   35.84   31.64   22.55
   22.35   23.04      25    32.2   33.54    33.9   33.32   33.14   33.12   34.61
   36.92   37.16   31.64    31.7   33.39   32.63   34.36   35.73   38.36   38.41
  2212.9  2242.9  2257.9  2347.9  2367.9  2392.9  2592.9  2602.9  2627.9  2642.9
  2692.9  2947.9  2977.9  3082.9  3482.9  3517.9  3577.9  3602.9  3622.9  3844.5
  3854.5  3874.5  3894.5  3944.5  3959.5  4258.4  4413.4  4433.4  4598.4  4673.4
  4703.4  4718.4  4733.4  4823.4  4838.4  4843.5  4858.4  4921.2  4974.8  4994.1
  5001.7  5005.9  5011.8  5025.4  5078.7  5142.4  5188.3  5257.2  5287.2  5312.2
  5333.6  5348.6  5528.6  5558.6  5633.6  5708.6  5783.6  5798.6  5813.6  5843.6
   37.42   35.14   35.07      38   37.98   36.73   37.41   37.14   35.37   35.07
   36.74   36.23    36.6   35.18   36.37   34.94   34.72   35.47   35.21   37.04
   36.56    34.5   33.87   34.32   34.92   36.24   36.08   36.36   34.27   34.77
   36.58   34.23   33.78   34.98    35.5   36.26   36.92   36.45    33.1   33.14
   33.15   33.16   33.17    33.2   34.15   34.51   33.75   33.73   35.22   37.53
   37.77   37.59   32.25   32.31      34   33.24   34.97   36.34   38.97   39.02
   37.42   35.14   35.07      38   37.98   36.73   37.41   37.14   35.37   35.07
   36.74   36.23    36.6   35.18   36.37   34.94   34.72   35.47   35.21   37.04
   36.56    34.5   33.87   34.32   34.92   36.24   36.08   36.36   34.27   34.77
   36.58   34.23   33.78   34.98    35.5   35.86   36.92   36.45   32.25   23.16
   22.96   23.65   25.61   32.81   34.15   34.51   33.75   33.73   35.22   37.53
   37.77   37.59   32.25   32.31      34   33.24   34.97   36.34   38.97   39.02
BR Coef= 1 , 0 , 0 ,1.25, 0 ,,,0.8,-1,2,0,
Wspro=,,,, 1 ,,,, 0 ,,,, 0 ,,,,-1 ,-1 ,-1 , 0 , 0 , 0 , 0 , 0
Culvert=4,8.0,6.0,30.0,0.015,0.9,1.0,29,1,22.61,4994.70,23.16,4994.70,Culvert #1  ,0,10
Culvert=4,8.0,6.0,30.0,0.015,0.9,1.0,29,1,22.40,5005.20,22.78,5005.20,Culvert #2  ,0,10
BC Design=,, 0 ,, 0 ,,,,,,
BR U #Sta/Elev= 89
  2212.9   36.81  2242.9   34.53  2257.9   34.46  2347.9   37.39  2367.9   37.37
  2392.9   36.12  2592.9    36.8  2602.9   36.53  2622.9   35.02  2627.9   34.76
  2637.9   34.49  2642.9   34.46  2692.9   36.13  2947.9   35.62  2977.9   35.99
  3037.9      35  3052.9   35.07  3082.9   34.57  3482.9   35.76  3517.9   34.33
  3577.9   34.11  3602.9   34.86  3607.9    34.9  3622.9    34.6  3809.5   35.92
  3844.5   36.43  3849.5   36.35  3854.5   35.95  3874.5   33.89  3894.5   33.26
  3944.5   33.71  3959.5   34.31  4258.4   35.63  4413.4   35.47  4427.7   35.67
  4433.4   35.75  4598.4   33.66  4673.4   34.16  4703.4   35.97  4708.4   35.29
  4718.4   33.62  4723.4   33.33  4733.4   33.17  4823.4   34.37  4838.4   34.89
  4843.5   35.25  4858.4   36.31  4862.6   36.28  4863.1   36.28  4921.2   35.84
    4923    35.7  4972.2   31.84  4974.8   31.64  4988.2   25.17  4994.1   22.55
  5001.7   22.35  5005.9   23.04  5011.8      25  5024.1   31.51  5025.4    32.2
  5047.3    32.9  5073.5   33.43  5078.7   33.54  5101.6   33.67  5132.5   33.84
  5142.4    33.9  5147.7   33.81  5177.4   33.32  5188.3   33.14  5188.4   33.14
  5257.2   33.12  5272.2   33.68  5287.2   34.61  5312.2   36.92  5313.6   36.99
  5323.6   36.92  5333.6   37.16  5338.6   37.03  5348.6   36.98  5528.6   31.64
  5558.6    31.7  5633.6   33.39  5708.6   32.63  5783.6   34.36  5788.6   34.89
  5798.6   35.73  5808.6   37.56  5813.6   38.36  5843.6   38.41
BR U #Mann= 7
 2212.90    0.99  4427.7     0.2  4927.7     0.1  4974.8    0.04  5025.4    0.11
  5050.8     0.1  5147.7       1
BR U Banks=4974.80,5025.40
BR D #Sta/Elev= 89
  2212.9   37.42  2242.9   35.14  2257.9   35.07  2347.9      38  2367.9   37.98
  2392.9   36.73  2592.9   37.41  2602.9   37.14  2622.9   35.63  2627.9   35.37
  2637.9    35.1  2642.9   35.07  2692.9   36.74  2947.9   36.23  2977.9    36.6
  3037.9   35.61  3052.9   35.68  3082.9   35.18  3482.9   36.37  3517.9   34.94
  3577.9   34.72  3602.9   35.47  3607.9   35.51  3622.9   35.21  3809.5   36.53
  3844.5   37.04  3849.5   36.96  3854.5   36.56  3874.5    34.5  3894.5   33.87
  3944.5   34.32  3959.5   34.92  4258.4   36.24  4413.4   36.08  4427.7   36.28
  4433.4   36.36  4598.4   34.27  4673.4   34.77  4703.4   36.58  4708.4    35.9
  4718.4   34.23  4723.4   33.94  4733.4   33.78  4823.4   34.98  4838.4    35.5
  4843.5   35.86  4858.4   36.92  4862.6   36.89  4863.1   36.89  4921.2   36.45
    4923   36.31  4972.2   32.45  4974.8   32.25  4988.2   25.78  4994.1   23.16
  5001.7   22.96  5005.9   23.65  5011.8   25.61  5024.1   32.12  5025.4   32.81
  5047.3   33.51  5073.5   34.04  5078.7   34.15  5101.6   34.28  5132.5   34.45
  5142.4   34.51  5147.7   34.42  5177.4   33.93  5188.3   33.75  5188.4   33.75
  5257.2   33.73  5272.2   34.29  5287.2   35.22  5312.2   37.53  5313.6    37.6
  5323.6   37.53  5333.6   37.77  5338.6   37.64  5348.6   37.59  5528.6   32.25
  5558.6   32.31  5633.6      34  5708.6   33.24  5783.6   34.97  5788.6    35.5
  5798.6   36.34  5808.6   38.17  5813.6   38.97  5843.6   39.02
BR D #Mann= 7
 2212.90    0.99  4427.7     0.2  4927.7     0.1  4974.8    0.04  5025.4    0.11
  5050.8     0.1  5147.7       1
BR D Banks=4974.80,5025.40

Type RM Length L Ch R = 1 ,10629.1,120.7,120.7,120.7
XS GIS Cut Line= 6
      3154227.83     13851781.29      3154553.43     13850228.67
      3154900.76     13849935.74      3154963.12     13849155.42
      3154823.34     13848929.33      3154783.15     13848403.36
BEGIN DESCRIPTION:
Downstream Section of Bridge/Culvert/Weir
END DESCRIPTION:
#Sta/Elev= 30
  2212.9   37.43  2257.9   35.08  2347.9   38.01  2592.9   37.42  2642.9   35.08
  2692.9   36.75  3082.9   35.19  3482.9   36.38  3577.9   34.73  3844.5   37.05
  3894.5   33.88  4427.7   36.29  4598.4   34.28  4703.4   36.59  4733.4   33.79
  4863.1    36.9  4921.2   36.46  4974.8   32.26  4994.1   23.17  5001.7   22.97
  5011.8   25.62  5025.4   32.82  5147.7   34.43  5257.2   33.74  5333.6   37.78
  5528.6   32.26  5708.6   33.25  5783.6   34.98  5813.6   38.98  5843.6   39.03
#Mann= 7 , 1 , 0
 2212.90    0.99       0  4427.7     0.2       0  4927.7     0.1       0
  4974.8    0.04       0  5025.4    0.11       0  5050.8     0.1       0
  5147.7       1       0
#XS Ineff= 2 , 0
       0 4968.13   33.09 5032.07       0   31.64
Bank Sta=4974.80,5025.40
Exp/Cntr=0.5,0.3

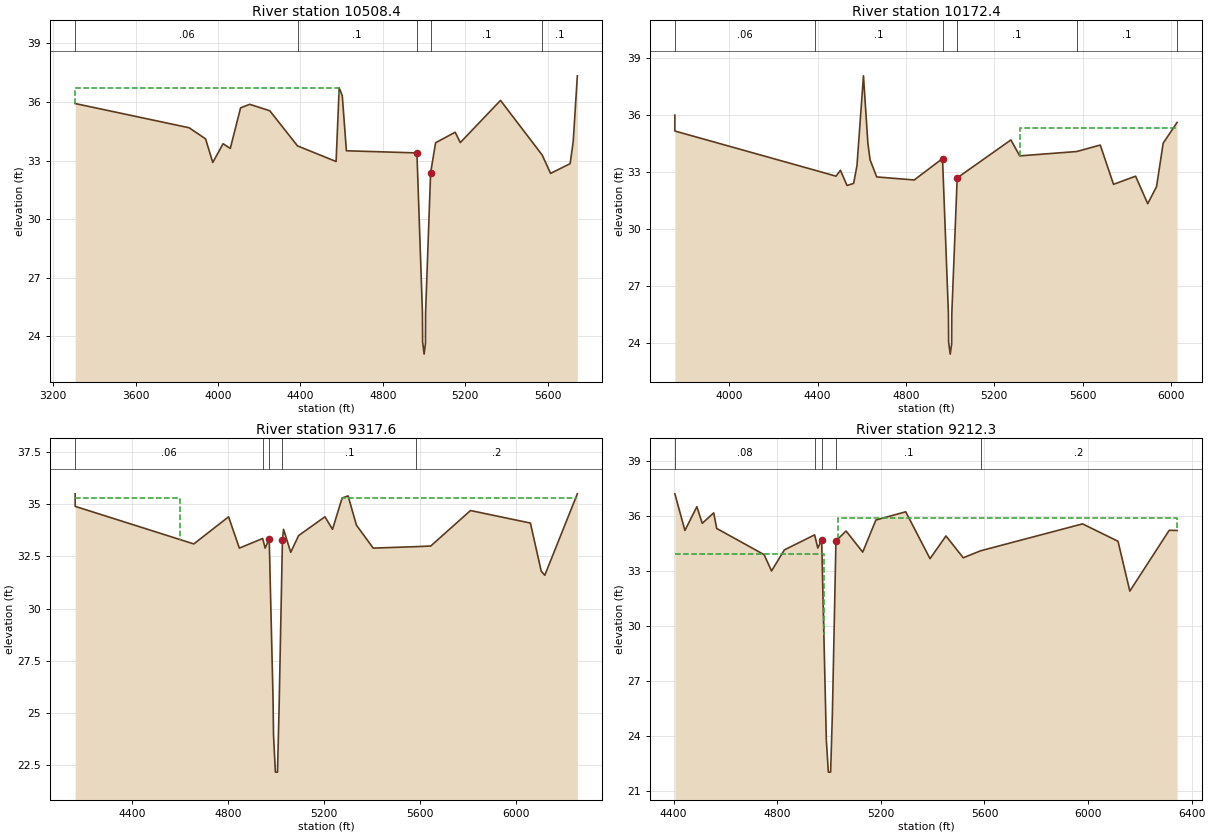
Type RM Length L Ch R = 1 ,10508.4,466.9,336,322.5
XS GIS Cut Line= 6
      3154756.74     13850832.22      3154756.36     13850279.22
      3155028.33     13849636.74      3155079.57     13849297.76
      3155099.28     13848805.06      3154971.32     13848479.36
BEGIN DESCRIPTION:
Cross Section 10508.4 - Interpolated
END DESCRIPTION:
#Sta/Elev= 30
  3306.9   35.92  3859.9   34.68  3939.9   34.11  3974.9    32.9  4024.9   33.86
  4059.9   33.62  4109.9    35.7  4154.3   35.88  4251.6   35.55  4386.1   33.75
  4573.4   32.95  4588.4   36.72  4603.4   36.32  4623.4    33.5  4965.7   33.39
  4992.4   25.22  4993.4    23.7  5000.6   23.08  5007.1   23.62  5007.7   25.19
  5032.2   32.37  5056.3   33.91  5151.3   34.45  5176.3   33.92  5371.4   36.08
  5573.8   33.28  5614.3   32.34  5709.3   32.84  5724.3   33.97  5744.3   37.34
#Mann= 5 , 1 , 0
 3306.90    0.06       0  4386.1     0.1       0  4965.7    0.04       0
  5032.2     0.1       0  5573.8     0.1       0
#XS Ineff= 2 , 0
       0    4587    36.7               0
Bank Sta=4965.70,5032.20
Exp/Cntr=0.3,0.1

Type RM Length L Ch R = 1 ,10172.4,855.3,854.8,802.3
XS GIS Cut Line= 4
      3155725.90     13850418.45      3155458.31     13849622.89
      3155400.45     13849022.60      3155357.05     13848190.88
BEGIN DESCRIPTION:
Cross Section 10172.4
Located At: 2ND XS DS E LOOP 610
END DESCRIPTION:
#Sta/Elev= 30
    3753      36  3753.1   35.16  4386.1    33.1  4483.1   32.78  4503.1   33.09
  4533.1   32.29  4563.1    32.4  4578.1   33.34  4607.5   38.07  4627.5   34.52
  4637.5   33.64  4667.5   32.74  4837.5   32.58  4965.7   33.71  4992.4   25.54
  4993.4   24.02  5000.6    23.4  5007.1   23.94  5007.7   25.51  5032.2   32.69
  5275.5   34.69  5315.5   33.85  5573.8   34.08  5680.5   34.42  5740.5   32.35
  5840.5   32.78  5895.5   31.33  5935.5   32.23  5965.5   34.52  6028.4   35.61
#Mann= 6 , 1 , 0
 3753.00    0.06       0  4386.1     0.1       0  4965.7    0.04       0
  5032.2     0.1       0  5573.8     0.1       0  6028.4     0.2       0
#XS Ineff= 2 , 0
       0                    5315       0    35.3
Bank Sta=4965.70,5032.20
Exp/Cntr=0.3,0.1

Type RM Length L Ch R = 1 ,9317.6,185.2,105.3,41.7
XS GIS Cut Line= 6
      3156239.19     13850097.12      3156267.57     13849229.96
      3156207.66     13849211.04      3156056.30     13849056.53
      3155911.25     13848577.24      3155837.96     13848137.51
BEGIN DESCRIPTION:
Cross Section 9317.6 - Interpolated
END DESCRIPTION:
#Sta/Elev= 30
  4161.8    35.5  4161.9    34.9  4656.9    33.1  4801.9    34.4  4846.9    32.9
  4944.2   33.36  4954.4    32.9  4971.4   33.35  4987.3   25.71  4989.4   23.94
  4997.2   22.17    5006   22.17  5012.8   25.34  5026.6   33.29  5031.2    33.8
  5061.2    32.7    5094    33.5    5204    34.4  5235.5    33.8  5275.5    35.3
  5300.5    35.4  5335.3      34  5405.3    32.9    5585   32.97  5645.3      33
  5811.1    34.7  6061.1    34.1  6106.1    31.8  6121.1    31.6  6256.9    35.5
#Mann= 5 , 1 , 0
 4161.80    0.06       0  4944.2     0.1       0  4971.4    0.04       0
  5026.6     0.1       0    5585     0.2       0
#XS Ineff= 2 , 0
       0    4600    35.3    5273       0    35.3
Bank Sta=4971.40,5026.60
Exp/Cntr=0.5,0.3

Type RM Length L Ch R = 1 ,9212.3,85,85,85
XS GIS Cut Line= 6
      3156581.42     13849811.62      3156475.74     13849424.68
      3156359.21     13849236.30      3156046.92     13849016.85
      3155924.34     13848594.18      3155844.04     13848112.35
BEGIN DESCRIPTION:
Upstream Section of Bridge/Culvert/Weir
END DESCRIPTION:
#Sta/Elev= 30
  4404.6   37.21  4443.4   35.21  4489.6   36.51  4510.3    35.6  4554.6   36.17
  4566.1   35.32  4749.2   33.89  4777.9      33  4827.4   34.15  4944.2   34.97
  4956.5   34.25  4971.4    34.7  4989.4   23.79  4997.2   22.02    5006   22.02
  5012.8   25.19  5026.6   34.64  5065.7   35.18    5130   34.03  5180.8   35.78
    5296   36.23  5389.8   33.67  5451.4   34.91  5518.2   33.72    5585    34.1
  5978.8   35.57  6115.7   34.62  6161.3    31.9  6313.4   35.22  6343.7   35.21
#Mann= 5 , 1 , 0
 4404.60    0.08       0  4944.2     0.1       0  4971.4    0.04       0
  5026.6     0.1       0    5585     0.2       0
#XS Ineff= 2 , 0
       0    4980    33.9    5033       0    35.9
Bank Sta=4971.40,5026.60
Exp/Cntr=0.5,0.3