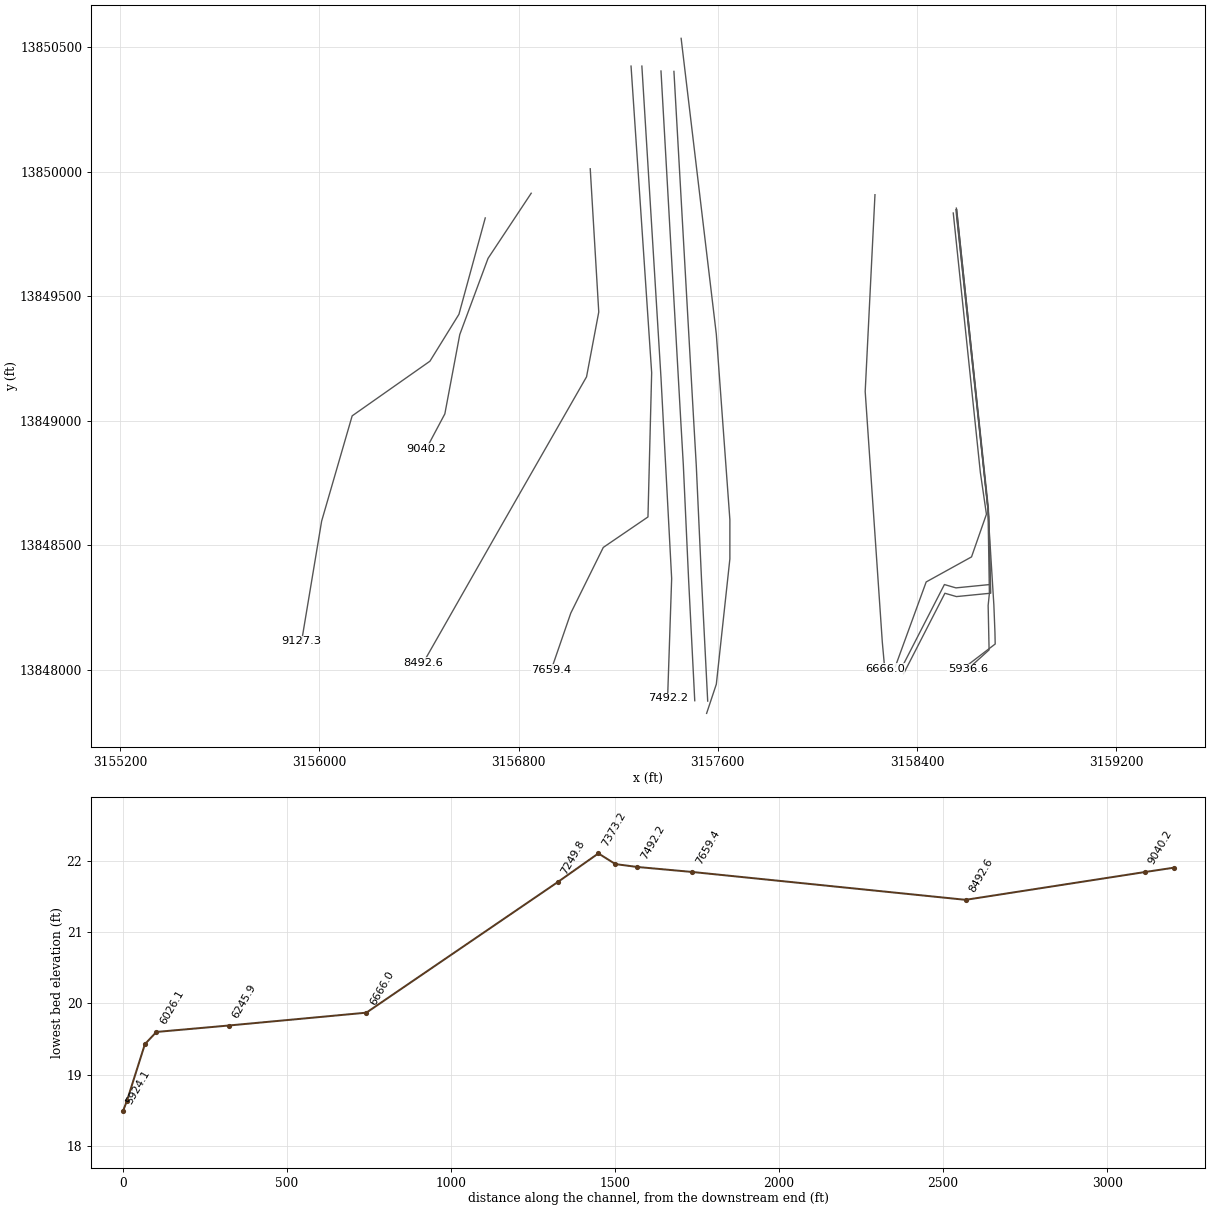
HEC-RAS study H103-00-00.PRJ: H103-00-00

--- H103-00-00.g01 (geometry) --- (continued)

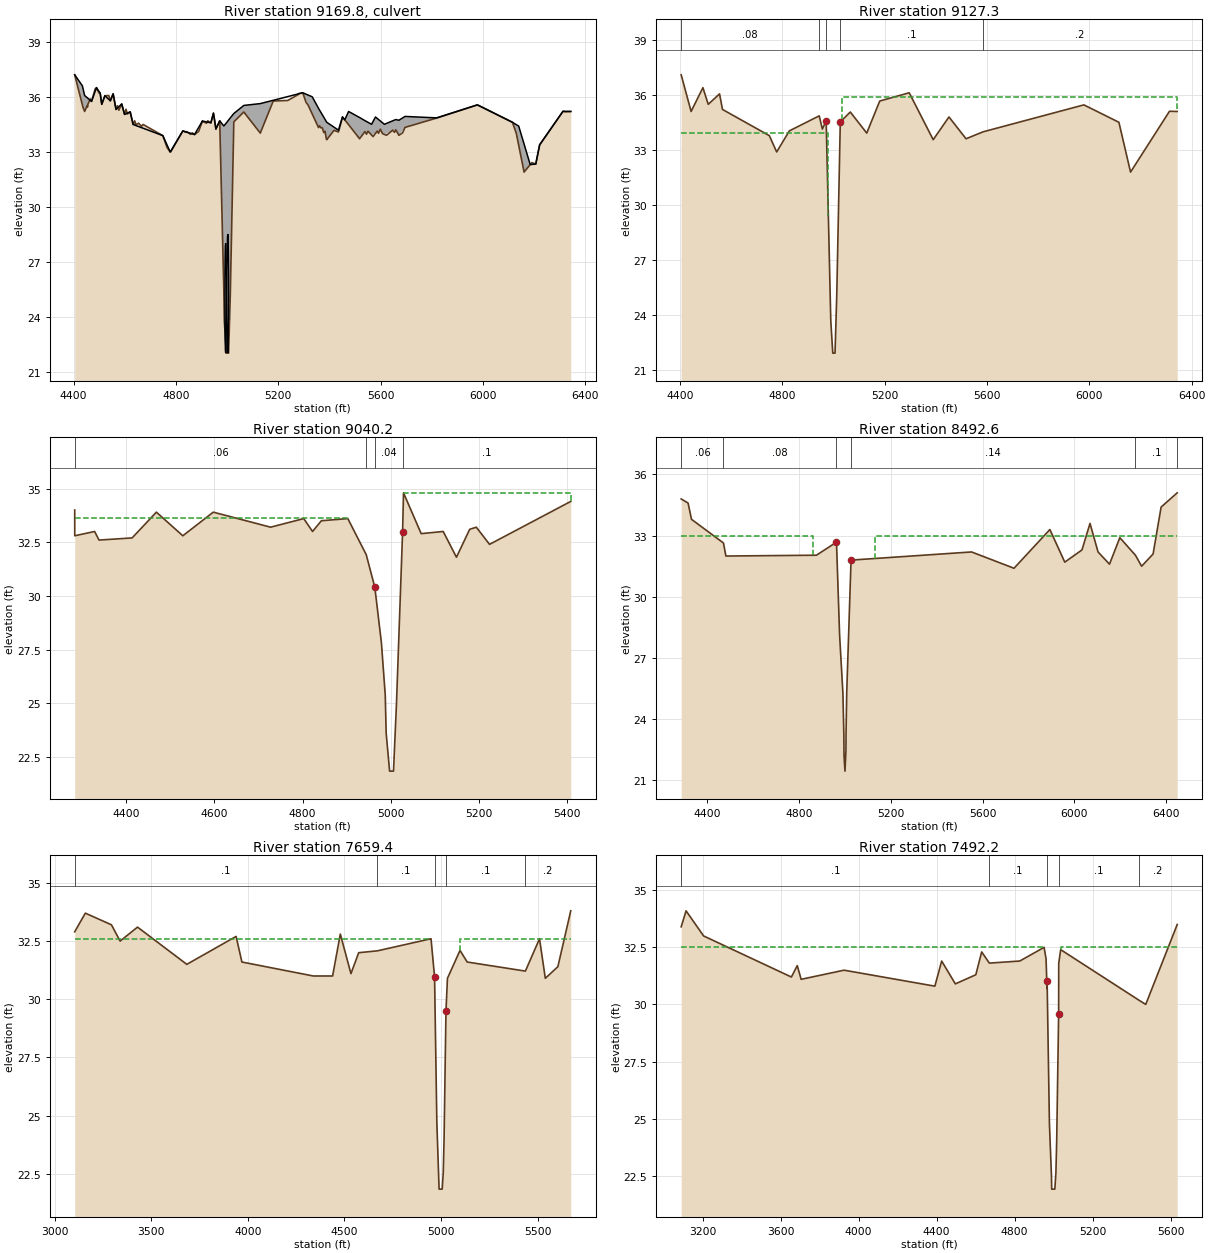
Type RM Length L Ch R = 2 ,9169.8,,,
BEGIN DESCRIPTION:
Access Road
Structure ID: H03-7
END DESCRIPTION:
Bridge Culvert--1,0,-1,-1, 0
Deck Dist Width WeirC Skew NumUp NumDn MinLoCord MaxHiCord MaxSubmerge Is_Ogee
10,65,3,, 60, 60,,,0.95,0,1,1,,
  4404.6  4434.6  4443.4  4470.4  4489.6  4504.1  4510.3  4522.6  4543.8  4554.6
  4566.1  4588.3  4599.5  4621.3  4632.9  4749.2  4777.9  4827.4  4872.9  4903.8
  4936.9    4947  4956.5  4971.4  4987.3  4989.4  4997.2    5006  5012.8  5026.6
  5065.7    5130  5180.8    5296  5333.1  5357.7  5383.1  5389.8  5435.7  5451.4
  5460.2  5475.2  5518.2  5539.1  5565.2  5580.2  5615.2  5659.7  5671.8  5695.9
  5819.5  5978.8  6115.7  6140.2  6161.3  6185.2  6206.9  6222.1  6313.4  6343.7
    37.2    36.6   36.07   35.75    36.5    36.2   35.59   36.06   35.78   36.16
   35.31   35.61   35.04   35.18   34.49   33.88   32.99   34.14   33.94   34.68
   34.58   35.11   34.24   34.69   34.41   34.44   34.57   34.73   34.85   35.09
   35.53   35.63   35.81   36.22      36   35.37   34.77   34.61   34.18    34.9
   34.74    35.2   34.87    34.7    34.5    34.9    34.5   34.76   34.72   34.93
   34.85   35.56   34.61    34.4   33.42    32.3   32.33   33.38   35.21    35.2
    37.2   35.56    35.2   35.75    36.5    36.2   35.59   36.06   35.78   36.16
   35.31   35.61   35.04   35.18   34.49   33.88   32.99   34.14   33.94   34.68
   34.58   35.11   34.24   34.69   25.55   23.78   22.01   22.01   25.18   34.63
   35.17   34.02   35.77   36.22   35.06   34.32   34.12   33.66   34.08    34.9
   34.74   34.48   33.71    34.1   33.91      34   33.95    34.2    33.9   34.33
   34.84   35.56   34.61   33.35   31.89    32.3   32.33   33.38   35.21    35.2
  4404.6  4434.6  4443.4  4470.4  4489.6  4504.1  4510.3  4522.6  4543.8  4554.6
  4566.1  4588.3  4599.5  4621.3  4632.9  4749.2  4777.9  4827.4  4872.9  4903.8
  4936.9    4947  4956.5  4971.4  4987.3  4989.4  4997.2    5006  5012.8  5026.6
  5065.7    5130  5180.8    5296  5333.1  5383.1  5389.8  5415.2  5435.7  5451.4
  5460.2  5475.2  5518.2  5539.1  5565.2  5580.2  5615.2  5659.7  5671.8  5695.9
  5855.2  5978.8  6115.7  6140.2  6161.3  6185.2  6206.9  6222.1  6313.4  6343.7
    37.1    36.6   36.07   35.66   36.41   36.11    35.5   35.97   35.69   36.07
   35.22   35.52   34.95   35.09    34.4   33.79   32.96   34.05   33.85   34.59
   34.49   35.02   34.15    34.6   34.41   34.44   34.57   34.73   34.85   35.09
   35.53   35.63   35.81   36.13      36   34.77   34.61   34.02   34.18   34.81
   34.65    35.2   34.87    34.7    34.5    34.9    34.5   34.76   34.72   34.93
    34.9   35.47   34.52    34.4   33.42   32.21   32.24   33.29   35.12    35.1
    37.1   35.46    35.1   35.65    36.4    36.1   35.49   35.96   35.68   36.06
   35.21   35.51   34.94   35.08   34.39   33.78   32.89   34.04   33.84   34.58
   34.48   35.01   34.14   34.59   25.45   23.68   21.91   21.91   25.08   34.53
   35.07   33.92   35.67   36.12   34.96   34.02   33.56   34.01   33.98    34.8
   34.64   34.38   33.61      34   33.81    33.9   33.85    34.1    33.8   34.23
    34.9   35.46   34.51   33.25   31.79    32.2   32.23   33.28   35.11    35.1
BR Coef= 1 , 0 , 0 ,1.25, 0 ,,,0.8,-1,2,0,
Wspro=,,,, 1 ,,,, 0 ,,,, 0 ,,,,-1 ,-1 ,-1 , 0 , 0 , 0 , 0 , 0
Culvert=1,6.0,,65.0,0.015,0.9,1.0,1,3,22.01,4994.60,21.91,4994.60,Culvert #1  ,0,10
Culvert=1,6.5,,65.0,0.015,0.9,1.0,1,3,22.01,5003.00,22.57,5003.00,Culvert #2  ,0,10
BC Design=,, 0 ,, 0 ,,,,,,
BR U #Sta/Elev= 148
  4404.6    37.2  4434.6   35.56  4436.7   35.44  4443.4    35.2  4444.6   35.24
  4449.6    35.4  4453.5   35.52  4454.6   35.45  4456.7   35.61  4465.7   35.88
  4470.4   35.75  4474.6   35.95  4484.7   36.44  4487.2   36.45    4488    36.4
  4489.6    36.5  4494.6   36.35  4499.2   36.21  4504.1    36.2  4504.6   36.15
  4510.3   35.59  4522.6   36.06  4524.6   36.06  4537.8   36.07  4543.8   35.78
  4554.6   36.16  4554.9   36.13  4555.5   36.13  4566.1   35.31  4571.5   35.51
  4577.2   35.27  4588.3   35.61  4599.5   35.04  4605.2   35.32  4610.6   35.06
  4621.3   35.18  4621.8   35.16    4622   35.16  4632.9   34.49  4638.9   34.69
  4644.1   34.48  4654.2   34.56  4664.4   34.41  4666.6    34.4  4671.9   34.49
  4749.2   33.88  4765.5   33.23    4776   33.03  4777.9   32.99  4780.1      33
    4817   33.89  4827.4   34.14  4839.7   34.06    4842    34.1  4857.4   33.95
  4864.5   34.03  4869.5   33.98  4872.9   33.94  4889.2   34.11  4903.8   34.68
  4906.6   34.64  4920.3   34.56  4923.2   34.65  4924.5   34.69  4936.9   34.58
  4944.2   34.96    4947   35.11  4953.6   34.55  4956.5   34.24  4971.4   34.69
  4987.3   25.55  4989.4   23.78  4990.4   23.55  4997.2   22.01    5006   22.01
  5012.8   25.18  5026.6   34.63  5033.7   34.73  5065.7   35.17  5080.2   34.91
  5125.2   34.11    5130   34.02  5175.4   35.58  5180.8   35.77  5218.5   35.79
  5237.3    35.8    5277   36.11  5278.8   36.17    5296   36.22  5308.9    35.7
  5316.5   35.56  5333.1   35.06  5348.1   34.61  5357.7   34.32  5361.9   34.42
  5366.5   34.31  5372.5   34.31  5378.2   34.05  5383.1   34.12  5388.4   33.69
  5389.8   33.66  5415.2   34.11  5418.4   34.17  5435.7   34.08  5451.4    34.9
  5460.2   34.74  5475.2   34.48  5518.2   33.71  5539.1    34.1  5545.3   33.96
  5551.1   34.12  5565.2   33.91  5570.9   33.83  5580.2      34    5585   34.09
  5587.3   34.13  5592.2   34.01  5599.4   34.23  5607.9   33.99  5615.2   33.95
  5623.5    33.9  5645.2   34.15  5647.6   34.18  5654.8   34.06  5659.7    34.2
  5671.8    33.9  5680.2   33.98  5686.1   34.03  5690.2   34.16  5695.9   34.33
  5715.2   34.41  5819.5   34.84  5855.2      35  5978.8   35.56  6115.7   34.61
  6130.9      34  6140.2   33.35  6161.3   31.89  6170.2   32.04  6185.2    32.3
  6191.7   32.41  6206.9   32.33  6222.1   33.38  6230.2   33.54  6245.2   33.84
  6313.4   35.21  6321.1   35.18  6343.7    35.2
BR U #Mann= 5
 4404.60    0.08  4944.2     0.1  4971.4    0.04  5026.6     0.1    5585     0.2
BR U Banks=4971.40,5026.60
BR D #Sta/Elev= 148
  4404.6    37.1  4434.6   35.46  4436.7   35.34  4443.4    35.1  4444.6   35.14
  4449.6    35.3  4453.5   35.42  4454.6   35.35  4456.7   35.51  4465.7   35.78
  4470.4   35.65  4474.6   35.85  4484.7   36.34  4487.2   36.35    4488    36.3
  4489.6    36.4  4494.6   36.25  4499.2   36.11  4504.1    36.1  4504.6   36.05
  4510.3   35.49  4522.6   35.96  4524.6   35.96  4537.8   35.97  4543.8   35.68
  4554.6   36.06  4554.9   36.03  4555.5   36.03  4566.1   35.21  4571.5   35.41
  4577.2   35.17  4588.3   35.51  4599.5   34.94  4605.2   35.22  4610.6   34.96
  4621.3   35.08  4621.8   35.06    4622   35.06  4632.9   34.39  4638.9   34.59
  4644.1   34.38  4654.2   34.46  4664.4   34.31  4666.6    34.3  4671.9   34.39
  4749.2   33.78  4765.5   33.13    4776   32.93  4777.9   32.89  4780.1    32.9
    4817   33.79  4827.4   34.04  4839.7   33.96    4842      34  4857.4   33.85
  4864.5   33.93  4869.5   33.88  4872.9   33.84  4889.2   34.01  4903.8   34.58
  4906.6   34.54  4920.3   34.46  4923.2   34.55  4924.5   34.59  4936.9   34.48
  4944.2   34.86    4947   35.01  4953.6   34.45  4956.5   34.14  4971.4   34.59
  4987.3   25.45  4989.4   23.68  4990.4   23.45  4997.2   21.91    5006   21.91
  5012.8   25.08  5026.6   34.53  5033.7   34.63  5065.7   35.07  5080.2   34.81
  5125.2   34.01    5130   33.92  5175.4   35.48  5180.8   35.67  5218.5   35.69
  5237.3    35.7    5277   36.01  5278.8   36.07    5296   36.12  5308.9    35.6
  5316.5   35.46  5333.1   34.96  5348.1   34.51  5357.7   34.22  5361.9   34.32
  5366.5   34.21  5372.5   34.21  5378.2   33.95  5383.1   34.02  5388.4   33.59
  5389.8   33.56  5415.2   34.01  5418.4   34.07  5435.7   33.98  5451.4    34.8
  5460.2   34.64  5475.2   34.38  5518.2   33.61  5539.1      34  5545.3   33.86
  5551.1   34.02  5565.2   33.81  5570.9   33.73  5580.2    33.9    5585   33.99
  5587.3   34.03  5592.2   33.91  5599.4   34.13  5607.9   33.89  5615.2   33.85
  5623.5    33.8  5645.2   34.05  5647.6   34.08  5654.8   33.96  5659.7    34.1
  5671.8    33.8  5680.2   33.88  5686.1   33.93  5690.2   34.06  5695.9   34.23
  5715.2   34.31  5819.5   34.74  5855.2    34.9  5978.8   35.46  6115.7   34.51
  6130.9    33.9  6140.2   33.25  6161.3   31.79  6170.2   31.94  6185.2    32.2
  6191.7   32.31  6206.9   32.23  6222.1   33.28  6230.2   33.44  6245.2   33.74
  6313.4   35.11  6321.1   35.08  6343.7    35.1
BR D #Mann= 5
 4404.60    0.08  4944.2     0.1  4971.4    0.04  5026.6     0.1    5585     0.2
BR D Banks=4971.40,5026.60

Type RM Length L Ch R = 1 ,9127.3,87.1,87.1,87.1
XS GIS Cut Line= 6
      3156666.36     13849815.02      3156560.68     13849428.08
      3156444.15     13849239.70      3156131.86     13849020.25
      3156009.28     13848597.58      3155928.98     13848115.75
BEGIN DESCRIPTION:
Downstream Section of Bridge/Culvert/Weir
END DESCRIPTION:
#Sta/Elev= 30
  4404.6   37.09  4443.4   35.09  4489.6   36.39  4510.3   35.48  4554.6   36.05
  4566.1    35.2  4749.2   33.77  4777.9   32.88  4827.4   34.03  4944.2   34.85
  4956.5   34.13  4971.4   34.58  4989.4   23.67  4997.2    21.9    5006    21.9
  5012.8   25.07  5026.6   34.52  5065.7   35.06    5130   33.91  5180.8   35.66
    5296   36.11  5389.8   33.55  5451.4   34.79  5518.2    33.6    5585   33.98
  5978.8   35.45  6115.7    34.5  6161.3   31.78  6313.4    35.1  6343.7   35.09
#Mann= 5 , 1 , 0
 4404.60    0.08       0  4944.2     0.1       0  4971.4    0.04       0
  5026.6     0.1       0    5585     0.2       0
#XS Ineff= 2 , 0
       0    4980    33.9    5033       0    35.9
Bank Sta=4971.40,5026.60
Exp/Cntr=0.5,0.3

Type RM Length L Ch R = 1 ,9040.2,515.8,547.6,549.5
XS GIS Cut Line= 5
      3156850.92     13849914.23      3156677.49     13849652.50
      3156563.98     13849346.64      3156504.06     13849028.15
      3156428.95     13848886.86
BEGIN DESCRIPTION:
Cross Section 9040.2 - Interpolated
END DESCRIPTION:
#Sta/Elev= 30
  4283.4      34  4283.5    32.8  4328.5      33  4338.5    32.6  4413.5    32.7
  4468.5    33.9  4528.5    32.8  4597.5    33.9  4727.5    33.2  4802.5    33.6
  4822.5      33  4842.5    33.5  4902.5    33.6  4944.2   31.92  4963.7    30.4
  4978.7    27.8  4987.3   25.38  4989.4   23.61  4997.2   21.84    5006   21.84
  5012.8   25.01  5026.6   32.96  5028.7    34.8  5068.7    32.9  5118.7      33
  5148.7    31.8  5178.7    33.1  5193.7    33.2  5223.7    32.4  5407.8    34.4
#Mann= 4 , 1 , 0
 4283.40    0.06       0  4944.2     0.1       0  4963.7    0.04       0
  5026.6     0.1       0
#XS Ineff= 2 , 0
       0    4900   33.65    5030       0    34.8
Bank Sta=4963.70,5026.60
Exp/Cntr=0.3,0.1

Type RM Length L Ch R = 1 ,8492.6,581.2,833.2,842.2
XS GIS Cut Line= 5
      3157087.95     13850012.44      3157122.18     13849437.10
      3157073.10     13849176.97      3156724.62     13848568.36
      3156417.77     13848029.37
BEGIN DESCRIPTION:
Cross Section  8492.6
Located At: 1ST XS US OATES
END DESCRIPTION:
#Sta/Elev= 30
    4286    34.8    4316    34.6    4331    33.8  4470.3   32.64    4481      32
  4875.7   32.04  4963.1   32.68  4976.7   28.12  4991.1   25.27  4995.2   23.22
  4995.9   22.21  5000.1   21.45  5004.3   22.44  5004.7   23.25  5007.8   25.34
  5026.6    31.8  5552.1    32.2  5737.1    31.4  5893.4    33.3  5958.4    31.7
  6033.4    32.3  6068.4    33.6  6103.4    32.2  6153.4    31.6  6198.4    32.9
  6266.4   32.04  6293.4    31.5  6343.4    32.1  6378.4    34.4  6448.6    35.1
#Mann= 6 , 1 , 0
 4286.00    0.06       0  4470.3    0.08       0  4963.1    0.04       0
  5026.6    0.14       0  6266.4     0.1       0  6448.6     0.2       0
#XS Ineff= 2 , 0
       0    4860      33    5130       0      33
Bank Sta=4963.10,5026.60
Exp/Cntr=0.3,0.1

Type RM Length L Ch R = 1 ,7659.4,74.6,167.2,263
XS GIS Cut Line= 6
      3157251.81     13850424.76      3157334.62     13849193.34
      3157319.78     13848614.27      3157140.36     13848491.94
      3157009.87     13848228.25      3156931.04     13847999.90
BEGIN DESCRIPTION:
Cross Section 7659.4 - Interpolated
END DESCRIPTION:
#Sta/Elev= 30
  3104.5    32.9  3159.5    33.7  3294.5    33.2  3339.5    32.5  3429.5    33.1
  3684.5    31.5  3939.5    32.7  3969.5    31.6  4338.7      31  4438.7      31
  4478.7    32.8  4533.7    31.1  4573.7      32  4670.1   32.08    4948    32.6
  4966.3   30.96  4978.1    24.7  4989.7   21.84  5005.7   21.84  5011.3   22.55
  5015.4   23.97  5025.3   29.49    5033    30.9    5098    32.1  5135.1    31.6
  5436.2   31.21  5509.3    32.6  5539.3    30.9  5604.3    31.4  5670.9    33.8
#Mann= 5 , 1 , 0
 3104.50     0.1       0  4670.1     0.1       0  4966.3    0.04       0
  5025.3     0.1       0  5436.2     0.2       0
#XS Ineff= 2 , 0
       0    4940    32.6    5100       0    32.6
Bank Sta=4966.30,5025.30
Exp/Cntr=0.3,0.1

Type RM Length L Ch R = 1 ,7492.2,65.9,67,71.9
XS GIS Cut Line= 4
      3157295.31     13850424.76      3157371.90     13849176.72
      3157414.92     13848366.89      3157398.61     13847885.72
BEGIN DESCRIPTION:
Cross Section 7492.2 - Interpolated
END DESCRIPTION:
#Sta/Elev= 30
  3090.4    33.4  3115.4    34.1  3205.4      33  3655.4    31.2  3685.4    31.7
  3705.4    31.1  3925.4    31.5  4390.8    30.8  4425.8    31.9  4495.8    30.9
  4600.8    31.3  4630.8    32.3  4670.1   31.81  4825.8    31.9  4950.8    32.5
  4960.8      32  4965.8    30.7  4966.3   31.03  4978.1   24.77  4988.7   22.45
  4989.7   21.91  5005.7   21.91  5011.3   22.62  5015.4   24.04  5025.3   29.56
  5025.8    31.8  5035.8    32.4  5436.2   30.19  5471.8      30  5633.2    33.5
#Mann= 5 , 1 , 0
 3090.40     0.1       0  4670.1     0.1       0  4966.3    0.04       0
  5025.3     0.1       0  5436.2     0.2       0
#XS Ineff= 2 , 0
       0    4950    32.5    5036       0    32.5
Bank Sta=4966.30,5025.30
Exp/Cntr=0.5,0.3

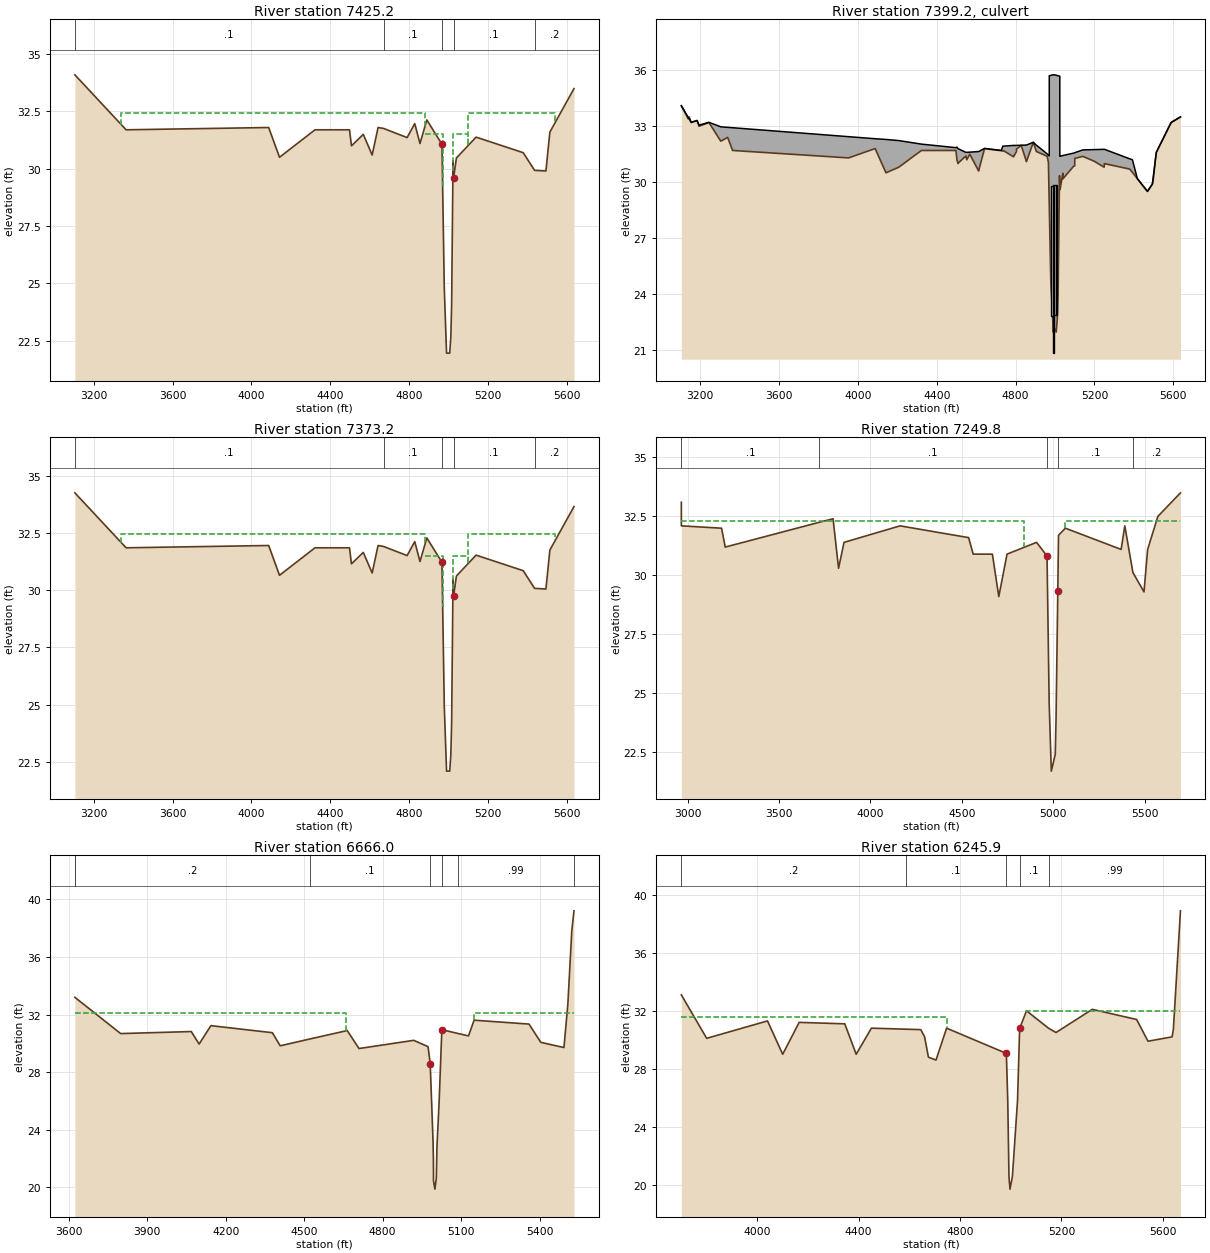
Type RM Length L Ch R = 1 ,7425.2,52,52,52
XS GIS Cut Line= 6
      3157372.08     13850405.00      3157408.25     13849765.21
      3157451.69     13848997.45      3157461.75     13848823.96
      3157482.90     13848364.37      3157507.67     13847876.35
BEGIN DESCRIPTION:
Upstream Section of Bridge/Culvert/Weir
END DESCRIPTION:
#Sta/Elev= 30
  3103.9    34.1  3363.9    31.7  4087.2    31.8  4142.2    30.5  4322.2    31.7
  4497.2    31.7  4507.2      31  4567.2    31.5  4612.2    30.6  4642.2    31.8
  4670.1   31.76  4789.4   31.36  4828.3   31.97  4854.8    31.1  4889.6   32.13
  4966.3   31.07  4978.1   24.81  4989.7   21.95  5005.7   21.95  5011.3   22.66
  5015.4   24.08  5022.5   30.34  5025.3    29.6  5039.7   30.47  5139.5   31.38
  5378.8    30.7  5436.2   29.93  5493.8    29.9  5513.8    31.6  5636.2    33.5
#Mann= 5 , 1 , 0
 3103.90     0.1       0  4670.1     0.1       0  4966.3    0.04       0
  5025.3     0.1       0  5436.2     0.2       0
#XS Ineff= 4 ,-1
    3340    4880   32.45  4880.1    4970    31.5    5022  5099.9    31.5
    5100    5542   32.45
Permanent Ineff=
       F       F       F       F
Bank Sta=4966.30,5025.30
Exp/Cntr=0.5,0.3

Type RM Length L Ch R = 2 ,7399.2,,,
BEGIN DESCRIPTION:
OATES ROAD
Structure ID: H03-6
END DESCRIPTION:
Bridge Culvert--1,0,-1,-1, 0
Deck Dist Width WeirC Skew NumUp NumDn MinLoCord MaxHiCord MaxSubmerge Is_Ogee
10,32,3,, 60, 60,,,0.95,0,1,1,,
  3103.9  3153.9  3183.9  3193.9  3243.9  3303.9  3338.9  3363.9  3952.2  4087.2
  4142.2  4207.2  4322.2  4497.2  4502.2  4507.2  4547.2  4552.2  4567.2  4612.2
  4642.2  4727.4  4734.8  4789.4  4804.4  4828.3  4854.8  4889.6  4905.5  4959.5
  4966.3 4970.49  4970.6  4978.1  4988.7  4989.7  4997.3  5005.7  5011.3  5015.4
  5022.5  5024.1 5024.21  5025.3  5039.7  5040.2  5040.3  5099.7  5100.1    5141
  5249.1  5251.1  5378.8  5392.5  5417.5  5468.8  5493.8  5513.8  5588.8  5636.2
    34.1   33.21   33.31   33.06   33.21   32.97   32.94   32.92   32.44   32.33
   32.29   32.23   32.04   31.85   31.88    31.8    31.6    31.6   31.61   31.64
   31.81    31.7   31.93   31.97   31.97   31.98   31.99   32.14   31.98   31.52
   31.45   31.41   35.71   35.73   35.76   35.76   35.76   35.74   35.72   35.71
   35.69   35.69   31.39   31.39   31.43   31.43   31.43   31.57   31.58   31.73
   31.76   31.76   31.25    31.2   30.19    29.5    29.9    31.6    33.2    33.5
    34.1    33.2    33.3      33    33.2    32.2    32.4    31.7    31.3    31.8
    30.5    30.8    31.7    31.7    31.2      31    31.4    31.2    31.5    30.6
    31.8   31.69   31.68   31.36   31.77   31.97    31.1   32.13   31.64   31.39
   31.07   28.85   28.79   24.81   22.49   21.95   22.15   21.95   22.66   24.08
   30.34   29.92   29.89    29.6   30.47   30.46   30.18   30.87   31.27   31.38
    30.8   30.99    30.7   30.52   30.18    29.5    29.9    31.6    33.2    33.5
  3103.9  3153.9  3183.9  3193.9  3243.9  3303.9  3338.9  3363.9  3952.2  4087.2
  4142.2  4207.2  4322.2  4497.2  4502.2  4507.2  4547.2  4552.2  4567.2  4612.2
  4642.2  4738.2  4789.4  4804.4  4828.3  4854.8  4889.6  4905.5  4959.5  4966.3
 4970.49  4970.6  4978.1  4988.7  4989.7  4997.3  5005.7  5011.3  5015.4  5022.5
  5024.1 5024.21  5025.3  5039.7  5040.2  5040.3  5099.7  5100.1    5141  5249.1
  5251.1  5378.8  5392.5  5407.5  5468.8  5493.8  5498.8  5513.8  5588.8  5636.2
   34.28   33.38   33.48   33.18   33.38   32.97   32.94   32.92   32.44   32.33
   32.29   32.23   32.04   31.88   31.88    31.8    31.6    31.6   31.68   31.64
   31.98   31.93   31.97   31.97   32.15   31.99   32.31   31.98   31.57   31.45
   31.41   35.71   35.73   35.76   35.76   35.76   35.74   35.72   35.71   35.69
   35.69   31.39   31.39   31.43   31.43   31.43   31.57   31.58   31.73   31.76
   31.76   31.25    31.2    30.5   29.68   30.08   30.38   31.78   33.38   33.68
   34.28   33.38   33.48   33.18   33.38   32.38   32.58   31.88   31.48   31.98
   30.68   30.98   31.88   31.88   31.38   31.18   31.58   31.38   31.68   30.78
   31.98   31.87   31.54   31.95   32.15   31.28   32.31   31.82   31.57   31.25
   29.03   28.97   24.99   22.67   22.13   22.33   22.13   22.84   24.26   30.52
    30.1   30.07   29.78   30.65   30.64   30.36   31.05   31.45   31.56   30.98
   31.17   30.88    30.7    30.5   29.68   30.08   30.38   31.78   33.38   33.68
BR Coef= 1 , 0 , 0 ,1.25, 0 ,,,0.8,-1,2,0,
Wspro=,,,, 1 ,,,, 0 ,,,, 0 ,,,,-1 ,-1 ,-1 , 0 , 0 , 0 , 0 , 0
Culvert=2,7.0,7.0,32.0,0.015,0.5,1.0,8,1,22.80,4985.10,22.83,4985.10,Culvert #1  ,0,10
Culvert=2,9.0,7.0,32.0,0.015,0.5,1.0,8,1,20.82,4992.80,20.85,4992.80,Culvert #2  ,0,10
Culvert=2,7.0,7.0,32.0,0.015,0.5,1.0,8,1,22.84,5000.40,22.87,5000.40,Culvert #3  ,0,10
Culvert=2,7.0,7.0,32.0,0.015,0.5,1.0,8,1,22.86,5008.00,22.89,5008.00,Culvert #4  ,0,10
BC Design=,, 0 ,, 0 ,,,,,,
BR U #Sta/Elev= 95
  3103.9    34.1  3138.9    33.4  3142.7   33.48  3143.9    33.5  3153.9    33.2
  3183.9    33.3  3193.9      33  3243.9    33.2  3303.9    32.2  3338.9    32.4
  3363.9    31.7  3952.2    31.3  4087.2    31.8  4142.2    30.5  4207.2    30.8
  4249.7   31.13  4279.7   31.37  4322.2    31.7  4489.7    31.7  4497.2    31.7
  4502.2    31.2  4504.7    31.1  4507.2      31  4509.7   31.03  4547.2    31.4
  4548.7   31.34  4552.2    31.2  4567.2    31.5  4607.2    30.7  4612.2    30.6
  4642.2    31.8  4670.1   31.76  4727.4   31.69  4734.8   31.68  4735.1   31.68
  4735.4   31.67  4738.2   31.69  4789.4   31.36  4790.4   31.38    4804   31.64
  4804.4   31.77  4828.3   31.97  4852.2   31.19  4854.8    31.1  4889.6   32.13
  4905.5   31.64  4906.3   31.64    4946   31.45  4959.5   31.39  4966.3   31.07
 4970.49   28.85  4970.6   28.79 4970.71   28.73  4978.1   24.81  4988.7   22.49
  4989.7   21.95  4994.3   22.07  4997.3   22.15  5005.7   21.95  5011.3   22.66
  5015.4   24.08  5022.5   30.34 5023.99   29.95  5024.1   29.92 5024.21   29.89
  5025.3    29.6  5039.7   30.47    5040   30.46  5040.2   30.46  5040.3   30.18
  5088.4   30.78  5093.9   30.85  5099.7   30.87  5100.1   31.27  5139.5   31.38
    5141   31.38  5196.9   31.13    5197   31.13  5249.1    30.8  5250.1   30.99
  5250.2   30.99  5251.1   30.99  5378.8    30.7  5392.5   30.52  5407.5   30.32
  5417.5   30.18  5436.1   29.94  5436.2   29.93  5468.8    29.5  5493.8    29.9
  5498.8    30.2  5508.8    31.2  5513.8    31.6  5588.8    33.2  5636.2    33.5
BR U #Mann= 5
 3103.90     0.1  4670.1     0.1  4966.3    0.04  5025.3     0.1  5436.2     0.2
BR U Banks=4966.30,5025.30
BR D #Sta/Elev= 95
  3103.9   34.28  3138.9   33.58  3142.7   33.66  3143.9   33.68  3153.9   33.38
  3183.9   33.48  3193.9   33.18  3243.9   33.38  3303.9   32.38  3338.9   32.58
  3363.9   31.88  3952.2   31.48  4087.2   31.98  4142.2   30.68  4207.2   30.98
  4249.7   31.31  4279.7   31.55  4322.2   31.88  4489.7   31.88  4497.2   31.88
  4502.2   31.38  4504.7   31.28  4507.2   31.18  4509.7   31.21  4547.2   31.58
  4548.7   31.52  4552.2   31.38  4567.2   31.68  4607.2   30.88  4612.2   30.78
  4642.2   31.98  4670.1   31.94  4727.4   31.87  4734.8   31.86  4735.1   31.86
  4735.4   31.85  4738.2   31.87  4789.4   31.54  4790.4   31.56    4804   31.82
  4804.4   31.95  4828.3   32.15  4852.2   31.37  4854.8   31.28  4889.6   32.31
  4905.5   31.82  4906.3   31.82    4946   31.63  4959.5   31.57  4966.3   31.25
 4970.49   29.03  4970.6   28.97 4970.71   28.91  4978.1   24.99  4988.7   22.67
  4989.7   22.13  4994.3   22.25  4997.3   22.33  5005.7   22.13  5011.3   22.84
  5015.4   24.26  5022.5   30.52 5023.99   30.13  5024.1    30.1 5024.21   30.07
  5025.3   29.78  5039.7   30.65    5040   30.64  5040.2   30.64  5040.3   30.36
  5088.4   30.96  5093.9   31.03  5099.7   31.05  5100.1   31.45  5139.5   31.56
    5141   31.56  5196.9   31.31    5197   31.31  5249.1   30.98  5250.1   31.17
  5250.2   31.17  5251.1   31.17  5378.8   30.88  5392.5    30.7  5407.5    30.5
  5417.5   30.36  5436.1   30.12  5436.2   30.11  5468.8   29.68  5493.8   30.08
  5498.8   30.38  5508.8   31.38  5513.8   31.78  5588.8   33.38  5636.2   33.68
BR D #Mann= 5
 3103.90     0.1  4670.1     0.1  4966.3    0.04  5025.3     0.1  5436.2     0.2
BR D Banks=4966.30,5025.30

Type RM Length L Ch R = 1 ,7373.2,123.4,123.4,123.4
XS GIS Cut Line= 6
      3157424.06     13850403.47      3157460.23     13849763.67
      3157503.67     13848995.91      3157513.73     13848822.42
      3157534.88     13848362.83      3157559.65     13847874.82
BEGIN DESCRIPTION:
Downstream Section of Bridge/Culvert/Weir
END DESCRIPTION:
#Sta/Elev= 30
  3103.9   34.25  3363.9   31.85  4087.2   31.95  4142.2   30.65  4322.2   31.85
  4497.2   31.85  4507.2   31.15  4567.2   31.65  4612.2   30.75  4642.2   31.95
  4670.1   31.91  4789.4   31.51  4828.3   32.12  4854.8   31.25  4889.6   32.28
  4966.3   31.22  4978.1   24.96  4989.7    22.1  5005.7    22.1  5011.3   22.81
  5015.4   24.23  5022.5   30.49  5025.3   29.75  5039.7   30.62  5139.5   31.53
  5378.8   30.85  5436.2   30.08  5493.8   30.05  5513.8   31.75  5636.2   33.65
#Mann= 5 , 1 , 0
 3103.90     0.1       0  4670.1     0.1       0  4966.3    0.04       0
  5025.3     0.1       0  5436.2     0.2       0
#XS Ineff= 4 ,-1
    3340    4880   32.45  4880.1    4970    31.5    5022  5099.9    31.5
    5100    5542   32.45
Permanent Ineff=
       F       F       F       F
Bank Sta=4966.30,5025.30
Exp/Cntr=0.5,0.3

Type RM Length L Ch R = 1 ,7249.8,600.3,583.8,583.6
XS GIS Cut Line= 6
      3157452.98     13850536.21      3157594.28     13849348.05
      3157648.71     13848603.40      3157648.71     13848445.73
      3157594.34     13847942.81      3157555.30     13847825.53
BEGIN DESCRIPTION:
Cross Section 7249.8 - Interpolated
END DESCRIPTION:
#Sta/Elev= 30
  2965.8    33.1  2965.9    32.1  3185.9      32  3205.9    31.2  3720.1   32.25
  3795.9    32.4  3825.9    30.3  3855.9    31.4  4162.4    32.1  4537.4    31.6
  4562.4    30.9  4667.4    30.9  4702.4    29.1  4747.4    30.9  4909.1    31.4
  4966.3   30.82  4978.1   24.56  4989.7    21.7  5011.3   22.41  5015.4   23.83
  5025.3   29.35  5029.1    31.7  5066.7      32  5371.7    31.1  5391.7    32.1
  5436.2   30.12  5496.7    29.3  5516.7    31.1  5572.6    32.5  5696.2    33.5
#Mann= 5 , 1 , 0
 2965.80     0.1       0  3720.1     0.1       0  4966.3    0.04       0
  5025.3     0.1       0  5436.2     0.2       0
#XS Ineff= 2 , 0
       0    4840    32.3    5067       0    32.3
Bank Sta=4966.30,5025.30
Exp/Cntr=0.3,0.1

Type RM Length L Ch R = 1 ,6666.0,484.8,420.1,360.7
XS GIS Cut Line= 4
      3158231.42     13849908.28      3158192.15     13849118.07
      3158260.87     13848111.91      3158270.68     13848003.93
BEGIN DESCRIPTION:
Cross Section  6666.0
Located At: 1ST XS US MERCURY
END DESCRIPTION:
#Sta/Elev= 30
  3623.3    33.2  3798.3   30.68  4068.3   30.82  4098.3   29.95  4143.3   31.23
  4378.3   30.74  4408.3   29.83  4523.3   30.31  4664.5   30.89  4709.5   29.64
  4918.6   30.21  4973.4   29.77  4981.7    28.6  4992.5   23.27  4994.1   21.73
  4994.3   20.45  4999.7   19.87  5005.2   20.66  5007.5   22.83  5015.8   25.91
  5026.2   30.95  5089.3   30.68  5128.2   30.52  5149.5   31.61  5359.5   31.34
  5404.5   30.07    5493   29.71    5508   32.74    5523   37.82  5531.4   39.21
#Mann= 7 , 1 , 0
 3623.30     0.2       0  3623.3     0.2       0  4523.3     0.1       0
  4981.7    0.04       0  5026.2    0.05       0  5089.3    0.99       0
  5531.4     0.2       0
#XS Ineff= 2 , 0
       0    4660    32.1    5150       0    32.1
Bank Sta=4981.70,5026.20
Exp/Cntr=0.3,0.1

Type RM Length L Ch R = 1 ,6245.9,20.2,219.8,86.4
XS GIS Cut Line= 6
      3158545.80     13849834.85      3158654.53     13848793.69
      3158679.00     13848625.14      3158619.19     13848453.88
      3158437.06     13848353.30      3158312.82     13848012.58
BEGIN DESCRIPTION:
Cross Section 6245.9 - Interpolated
END DESCRIPTION:
#Sta/Elev= 30
  3700.3    33.1  3800.3    30.1  4040.3    31.3  4100.3      29  4165.3    31.2
  4345.3    31.1  4390.3      29  4450.3    30.8  4585.7   30.73  4645.3    30.7
  4660.3    30.2  4675.3    28.8  4705.3    28.6  4747.1    30.8  4982.9   29.06
  4988.4    25.8  4993.3   20.52  4997.2   19.69  5006.7   20.56    5027   25.82
  5035.3   30.78  5062.4      32  5149.9   30.79  5178.8    30.5  5321.9    32.1
  5496.9    31.4  5541.9    29.9  5636.9    30.2  5641.9    30.7  5669.9    38.9
#Mann= 5 , 1 , 0
 3700.30     0.2       0  4585.7     0.1       0  4982.9    0.04       0
  5035.3     0.1       0  5149.9    0.99       0
#XS Ineff= 2 , 0
       0    4750    31.6    5060       0      32
Bank Sta=4982.90,5035.30
Exp/Cntr=0.5,0.3

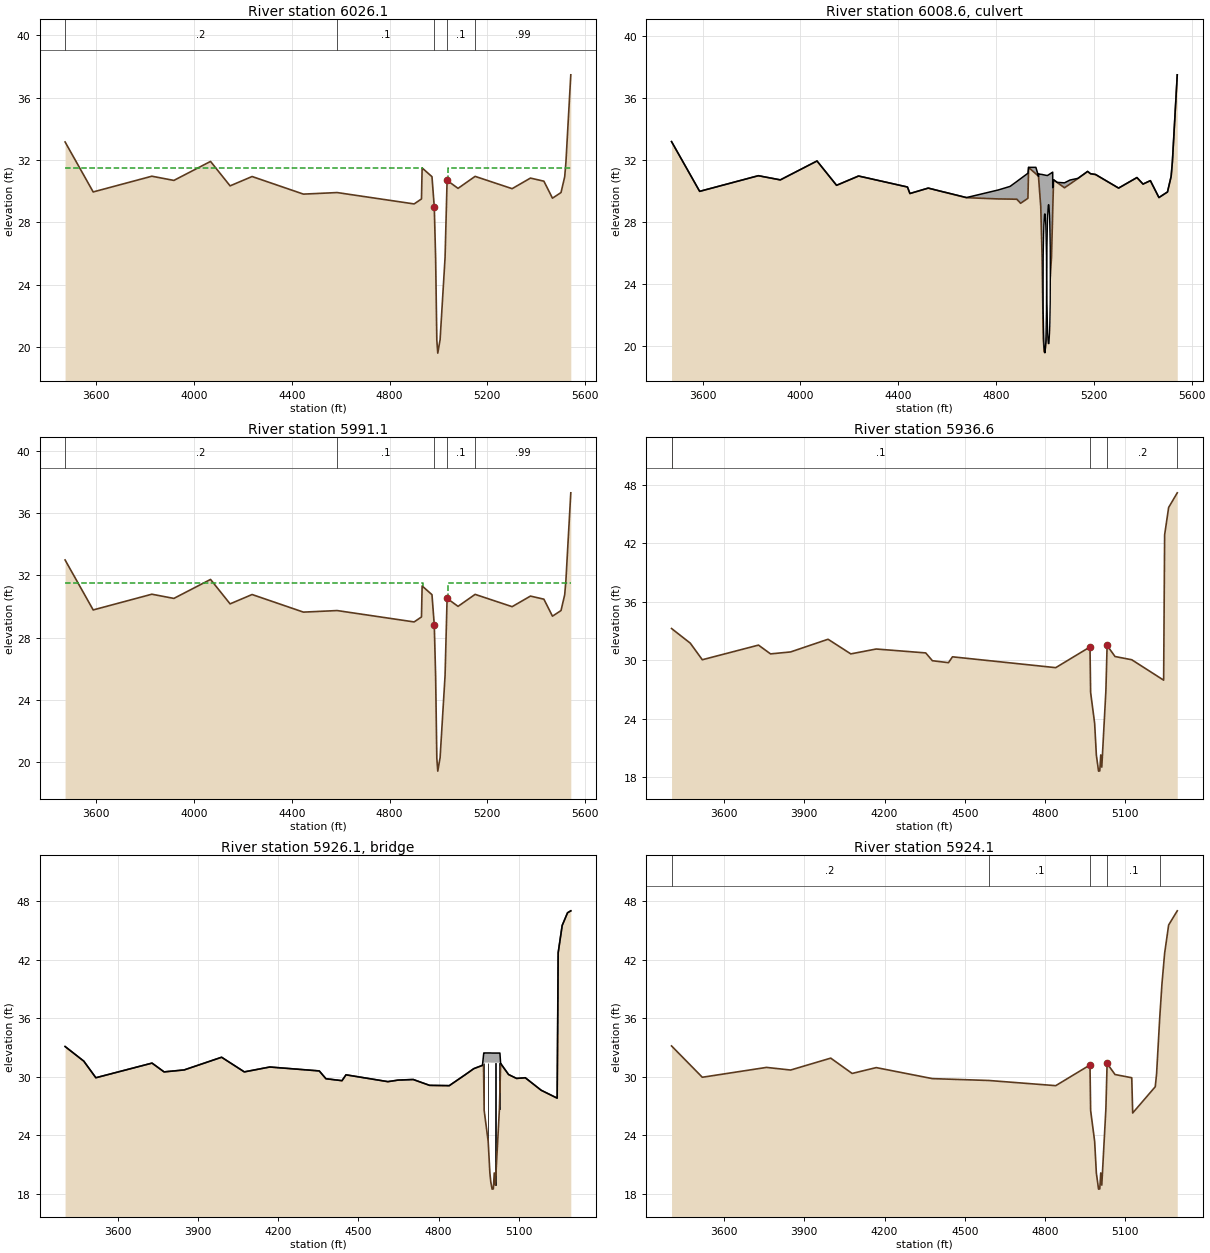
Type RM Length L Ch R = 1 ,6026.1,35,35,35
XS GIS Cut Line= 6
      3158558.29     13849854.34      3158686.83     13848649.34
      3158694.23     13848343.02      3158556.60     13848329.46
      3158510.25     13848342.85      3158344.06     13848019.24
BEGIN DESCRIPTION:
Upstream Section of Bridge/Culvert/Weir
END DESCRIPTION:
#Sta/Elev= 30
  3472.7   33.16  3587.7   29.95  3827.7   30.96  3917.7   30.69  4067.7   31.91
  4147.7   30.34  4237.7   30.94  4447.7   29.81  4585.7   29.91  4900.5   29.18
  4930.5    29.5  4933.2   31.49  4973.5   30.93  4982.9   28.97  4988.4   25.71
  4993.3   20.43  4997.2    19.6  5006.7   20.47    5027   25.73  5035.3   30.69
  5080.1   30.18  5149.9   30.95  5301.3   30.16  5376.3   30.84  5431.3   30.64
  5466.3   29.55  5501.3   29.91  5516.3   30.92  5521.3   31.84  5541.3   37.47
#Mann= 5 , 1 , 0
 3472.70     0.2       0  4585.7     0.1       0  4982.9    0.04       0
  5035.3     0.1       0  5149.9    0.99       0
#XS Ineff= 2 , 0
       0    4935    31.5    5040       0    31.5
Bank Sta=4982.90,5035.30
Exp/Cntr=0.5,0.3

Type RM Length L Ch R = 2 ,6008.6,,,
BEGIN DESCRIPTION:
PRIVATE DRIVE
Structure ID: H03-5
END DESCRIPTION:
Bridge Culvert--1,0,-1,-1, 0
Deck Dist Width WeirC Skew NumUp NumDn MinLoCord MaxHiCord MaxSubmerge Is_Ogee
10,15,3,,56,56,,,0.95,0,1,1,,
  3472.7  3587.7  3827.7  3917.7  4067.7  4147.7  4237.7  4437.7  4447.7  4522.7
  4585.7  4589.8  4679.2  4809.2  4857.4  4885.2  4900.5  4930.5  4933.2    4963
  4973.5 4973.59  4973.7 4973.81  4982.9  4988.4  4993.3  4997.2  5000.1  5003.2
  5006.7    5010    5027 5031.69  5031.8 5031.91  5035.3  5050.2  5080.1  5102.4
  5135.2  5149.9  5156.3  5174.5  5186.6  5207.7  5208.3  5301.3  5376.3  5401.3
  5431.3  5466.3  5501.3  5516.3  5521.3  5541.3
   33.16   29.95   30.96   30.69   31.91   30.34   30.94   30.23   29.81   30.16
   29.91    29.9   29.55   30.04   30.27   30.59   30.77   31.12    31.5    31.5
   30.94   30.92   31.08   31.08   31.05   31.04   31.02   31.01      31   30.99
   30.98   30.97   31.14   31.19   31.19   30.19    30.7   30.53    30.5   30.68
   30.79   30.96   31.03   31.24   31.09   31.04   31.03   30.16   30.84   30.42
   30.64   29.55   29.91   30.92   31.84   37.47
   33.16   29.95   30.96   30.69   31.91   30.34   30.94   30.23   29.81   30.16
   29.91   29.89   29.54   29.46   29.45   29.44   29.18    29.5   31.49   31.08
   30.93   30.91   30.89   30.87   28.97   25.71   20.43    19.6    19.6   20.09
   20.47   21.33   25.73   28.53    28.6   28.66   30.69   30.52   30.18   30.42
   30.78   30.95   31.02   31.23   31.08   31.03   31.02   30.16   30.84   30.42
   30.64   29.55   29.91   30.92   31.84   37.47
  3472.7  3587.7  3827.7  3917.7  4067.7  4147.7  4237.7  4437.7  4447.7  4522.7
  4585.7  4589.8  4679.2  4809.2  4857.4  4885.2  4900.5  4930.5  4933.2    4963
  4973.5 4973.59  4973.7 4973.81  4982.9  4988.4  4993.3  4997.2  5000.1  5003.2
  5006.7    5010    5027 5031.69  5031.8 5031.91  5035.3  5050.2  5080.1  5102.4
  5135.2  5149.9  5156.3  5174.5  5186.6  5207.7  5208.3  5301.3  5376.3  5401.3
  5431.3  5466.3  5501.3  5516.3  5521.3  5541.3
   33.16   29.95   30.96   30.69   31.91   30.34   30.94   30.23   29.81   30.16
   29.91    29.9   29.55   30.04   30.27   30.59   30.77   31.12    31.5    31.5
   30.94   30.92   31.08   31.08   31.05   31.04   31.02   31.01      31   30.99
   30.98   30.97   31.14   31.19   31.19   30.19    30.7   30.53    30.5   30.68
   30.79   30.96   31.03   31.24   31.09   31.04   31.03   30.16   30.84   30.42
   30.64   29.55   29.91   30.92   31.84   37.47
   33.13   29.92   30.93   30.66   31.88   30.31   30.91    30.2   29.78   30.13
   29.88   29.86   29.51   29.43   29.42   29.41   29.15   29.47   31.46   31.05
    30.9   30.88   30.86   30.84   28.94   25.68    20.4   19.57   19.57   20.06
   20.44    21.3    25.7    28.5   28.57   28.63   30.66   30.49   30.15   30.39
   30.75   30.92   30.99    31.2   31.05      31   30.99   30.13   30.81   30.39
   30.61   29.52   29.88   30.89   31.81   37.44
BR Coef= 1 , 0 , 0 ,1.25, 0 ,,,0.8,-1,2,0,
Wspro=,,,, 1 ,,,, 0 ,,,, 0 ,,,,-1 ,-1 ,-1 , 0 , 0 , 0 , 0 , 0
Culvert=4,9.0,14.0,15.0,0.015,0.9,1.0,29,1,19.51,4999.60,19.59,4999.60,Culvert #1  ,0,10
Culvert=4,9.0,14.0,15.0,0.015,0.9,1.0,29,1,20.10,5015.00,19.45,5015.00,Culvert #2  ,0,10
BC Design=,, 0 ,, 0 ,,,,,,
BR U #Sta/Elev= 56
  3472.7   33.16  3587.7   29.95  3827.7   30.96  3917.7   30.69  4067.7   31.91
  4147.7   30.34  4237.7   30.94  4437.7   30.23  4447.7   29.81  4522.7   30.16
  4585.7   29.91  4589.8   29.89  4679.2   29.54  4809.2   29.46  4857.4   29.45
  4885.2   29.44  4900.5   29.18  4930.5    29.5  4933.2   31.49    4963   31.08
  4973.5   30.93 4973.59   30.91  4973.7   30.89 4973.81   30.87  4982.9   28.97
  4988.4   25.71  4993.3   20.43  4997.2    19.6  5000.1    19.6  5003.2   20.09
  5006.7   20.47    5010   21.33    5027   25.73 5031.69   28.53  5031.8    28.6
 5031.91   28.66  5035.3   30.69  5050.2   30.52  5080.1   30.18  5102.4   30.42
  5135.2   30.78  5149.9   30.95  5156.3   31.02  5174.5   31.23  5186.6   31.08
  5207.7   31.03  5208.3   31.02  5301.3   30.16  5376.3   30.84  5401.3   30.42
  5431.3   30.64  5466.3   29.55  5501.3   29.91  5516.3   30.92  5521.3   31.84
  5541.3   37.47
BR U #Mann= 5
 3472.70     0.2  4585.7     0.1  4982.9    0.04  5035.3     0.1  5149.9    0.99
BR U Banks=4982.90,5035.30
BR D #Sta/Elev= 56
  3472.7   33.13  3587.7   29.92  3827.7   30.93  3917.7   30.66  4067.7   31.88
  4147.7   30.31  4237.7   30.91  4437.7    30.2  4447.7   29.78  4522.7   30.13
  4585.7   29.88  4589.8   29.86  4679.2   29.51  4809.2   29.43  4857.4   29.42
  4885.2   29.41  4900.5   29.15  4930.5   29.47  4933.2   31.46    4963   31.05
  4973.5    30.9 4973.59   30.88  4973.7   30.86 4973.81   30.84  4982.9   28.94
  4988.4   25.68  4993.3    20.4  4997.2   19.57  5000.1   19.57  5003.2   20.06
  5006.7   20.44    5010    21.3    5027    25.7 5031.69    28.5  5031.8   28.57
 5031.91   28.63  5035.3   30.66  5050.2   30.49  5080.1   30.15  5102.4   30.39
  5135.2   30.75  5149.9   30.92  5156.3   30.99  5174.5    31.2  5186.6   31.05
  5207.7      31  5208.3   30.99  5301.3   30.13  5376.3   30.81  5401.3   30.39
  5431.3   30.61  5466.3   29.52  5501.3   29.88  5516.3   30.89  5521.3   31.81
  5541.3   37.44
BR D #Mann= 5
 3472.70     0.2  4585.7     0.1  4982.9    0.04  5035.3     0.1  5149.9    0.99
BR D Banks=4982.90,5035.30

Type RM Length L Ch R = 1 ,5991.1,54.5,54.5,54.5
XS GIS Cut Line= 6
      3158560.29     13849819.39      3158688.83     13848614.40
      3158696.23     13848308.08      3158558.60     13848294.52
      3158512.25     13848307.91      3158346.06     13847984.29
BEGIN DESCRIPTION:
Downstream Section of Bridge/Culvert/Weir
END DESCRIPTION:
#Sta/Elev= 30
  3472.7   32.99  3587.7   29.78  3827.7   30.79  3917.7   30.52  4067.7   31.74
  4147.7   30.17  4237.7   30.77  4447.7   29.64  4585.7   29.74  4900.5   29.01
  4930.5   29.33  4933.2   31.32  4973.5   30.76  4982.9    28.8  4988.4   25.54
  4993.3   20.26  4997.2   19.43  5006.7    20.3    5027   25.56  5035.3   30.52
  5080.1   30.01  5149.9   30.78  5301.3   29.99  5376.3   30.67  5431.3   30.47
  5466.3   29.38  5501.3   29.74  5516.3   30.75  5521.3   31.67  5541.3    37.3
#Mann= 5 , 1 , 0
 3472.70     0.2       0  4585.7     0.1       0  4982.9    0.04       0
  5035.3     0.1       0  5149.9    0.99       0
#XS Ineff= 2 , 0
       0    4935    31.5    5040       0    31.5
Bank Sta=4982.90,5035.30
Exp/Cntr=0.5,0.3

Type RM Length L Ch R = 1 ,5936.6,12.5,12.5,12.5
XS GIS Cut Line= 6
      3158559.77     13849847.93      3158685.33     13848646.96
      3158690.92     13848307.43      3158685.93     13848258.81
      3158689.70     13848080.52      3158603.90     13848002.65
BEGIN DESCRIPTION:
Upstream Section of Bridge/Culvert/Weir
END DESCRIPTION:
#Sta/Elev= 30
    3404   33.25    3474   31.75    3519   30.05    3729   31.55    3774   30.65
    3849   30.85    3989   32.15    4074   30.65    4169   31.15    4354   30.75
    4379   29.95    4439   29.75    4454   30.35 4839.99   29.24 4967.99   31.36
 4970.39    26.7 4985.39   23.54 4991.79   20.29 4999.99   18.64 5004.59   18.66
 5008.19    20.3 5012.09   19.05 5027.39   26.85 5031.99   31.51 5061.59   30.38
 5124.09   30.05 5243.29   27.96    5247   42.85    5262   45.65  5294.2   47.15
#Mann= 5 , 1 , 0
 3404.00     0.2       0    3404     0.1       0 4967.99    0.04       0
 5031.99     0.2       0  5294.2     0.2       0
#XS Ineff= 2 , 0
       0    4960    31.1    5040       0      31
Bank Sta=4967.99,5031.99
Exp/Cntr=0.5,0.3

Type RM Length L Ch R = 3 ,5926.1,,,
BEGIN DESCRIPTION:
PIPELINE
END DESCRIPTION:
Bridge Culvert--1,0,-1,-1, 0
Deck Dist Width WeirC Skew NumUp NumDn MinLoCord MaxHiCord MaxSubmerge Is_Ogee
10,1,2.6,,48,48,,,0.95,0,1,1,,
    3404    3474    3519    3729    3774    3849    3989    4074    4169    4354
    4379    4439    4454  4610.5 4648.99 4705.19 4766.39 4839.99 4900.59 4931.49
 4963.99  4964.1 4964.19 4967.99 4968.89 4970.39 4985.39 4991.79 4995.09 4999.99
 5004.59 5008.19 5012.09 5027.39 5029.29 5031.99 5033.38 5033.49 5033.59 5061.59
 5091.49 5124.09 5183.39 5243.29    5247    5262    5282  5294.2
   33.11   31.61   29.91   31.41   30.51   30.71   32.01   30.51   31.01   30.61
   29.81   29.61   30.21   29.51   29.67   29.73   29.13    29.1   30.24   30.84
   31.18   31.21   31.23   32.22   32.45   32.45   32.45   32.45   32.45   32.44
   32.44   32.44   32.44   32.44   32.44   31.37   31.32   31.31   31.31   30.24
   29.84   29.91   28.63   27.82   42.71   45.51   46.81   47.01
   33.11   31.61   29.91   31.41   30.51   30.71   32.01   30.51   31.01   30.61
   29.81   29.61   30.21   29.51   29.67   29.73   29.13    29.1   30.24   30.84
   31.18   31.18   31.18   31.23   31.46   31.46   31.46   31.46   31.46   31.45
   31.45   31.45   31.45   31.45   31.45   31.37   31.32   31.31   31.31   30.24
   29.84   29.91   28.63   27.82   42.71   45.51   46.81   47.01
    3404    3474    3519    3729    3774    3849    3989    4074    4169    4354
    4379    4439    4454  4610.5 4648.99 4705.19 4766.39 4839.99 4900.59 4931.49
 4963.99  4964.1 4964.19 4967.99 4968.89 4970.39 4985.39 4991.79 4995.09 4999.99
 5004.59 5008.19 5012.09 5027.39 5029.29 5031.99 5033.38 5033.49 5033.59 5061.59
 5091.49 5124.09 5183.39 5243.29    5247    5262    5282  5294.2
    33.1    31.6    29.9    31.4    30.5    30.7      32    30.5      31    30.6
    29.8    29.6    30.2    29.5   29.66   29.72   29.12   29.09   30.23   30.83
   31.18   31.21   31.23   32.22   32.45   32.45   32.45   32.45   32.45   32.44
   32.44   32.44   32.44   32.44   32.44   31.36   31.32   31.31    31.3   30.23
   29.83    29.9   28.62   27.81    42.7    45.5    46.8      47
    33.1    31.6    29.9    31.4    30.5    30.7      32    30.5      31    30.6
    29.8    29.6    30.2    29.5   29.66   29.72   29.12   29.09   30.23   30.83
   31.17   31.17   31.17   31.22   31.45   31.45   31.45   31.45   31.45   31.44
   31.44   31.44   31.44   31.44   31.44   31.36   31.31    31.3    31.3   30.23
   29.83    29.9   28.62   27.81    42.7    45.5    46.8      47
Pier Skew, UpSta & Num, DnSta & Num=,4970.4, 2 ,4970.4, 2 , 0 , 0 , 0 ,,
     1.4     1.4
   25.41   32.46
     1.4     1.4
    25.4   32.45
Pier Skew, UpSta & Num, DnSta & Num=,4985.4, 2 ,4985.4, 2 , 0 , 0 , 0 ,,
     1.4     1.4
   22.04   32.46
     1.4     1.4
   22.03   32.45
Pier Skew, UpSta & Num, DnSta & Num=,5012.1, 2 ,5012.1, 2 , 0 , 0 , 0 ,,
     1.4     1.4
   18.13   32.45
     1.4     1.4
   18.12   32.44
Pier Skew, UpSta & Num, DnSta & Num=,5027.4, 2 ,5027.4, 2 , 0 , 0 , 0 ,,
     1.4     1.4
   25.35   32.45
     1.4     1.4
   25.34   32.44
BR Coef= 1 , 1 , 0 ,1.25, 0 ,,,0.8,0,2,0,
Wspro=,,,, 1 ,,,, 0 ,,,, 0 ,,,,-1 ,-1 ,-1 , 0 , 0 , 0 , 0 , 0
BC Design=,, 0 ,, 0 ,,,,,,
BR U #Sta/Elev= 48
    3404   33.11    3474   31.61    3519   29.91    3729   31.41    3774   30.51
    3849   30.71    3989   32.01    4074   30.51    4169   31.01    4354   30.61
    4379   29.81    4439   29.61    4454   30.21  4610.5   29.51 4648.99   29.67
 4705.19   29.73 4766.39   29.13 4839.99    29.1 4900.59   30.24 4931.49   30.84
 4963.99   31.18  4964.1   31.18 4964.19   31.18 4967.99   31.22 4968.89   29.47
 4970.39   26.56 4985.39    23.4 4991.79   20.15 4995.09   19.26 4999.99    18.5
 5004.59   18.52 5008.19   20.16 5012.09   18.91 5027.39   26.71 5029.29   28.63
 5031.99   31.37 5033.38   31.32 5033.49   31.31 5033.59   31.31 5061.59   30.24
 5091.49   29.84 5124.09   29.91 5183.39   28.63 5243.29   27.82    5247   42.71
    5262   45.51    5282   46.81  5294.2   47.01
BR U #Mann= 5
 3404.00     0.2    3404     0.1 4967.99    0.04 5031.99     0.2  5294.2     0.2
BR U Banks=4967.99,5031.99
BR D #Sta/Elev= 48
    3404    33.1    3474    31.6    3519    29.9    3729    31.4    3774    30.5
    3849    30.7    3989      32    4074    30.5    4169      31    4354    30.6
    4379    29.8    4439    29.6    4454    30.2  4610.5    29.5 4648.99   29.66
 4705.19   29.72 4766.39   29.12 4839.99   29.09 4900.59   30.23 4931.49   30.83
 4963.99   31.17  4964.1   31.17 4964.19   31.17 4967.99   31.21 4968.89   29.46
 4970.39   26.55 4985.39   23.39 4991.79   20.14 4995.09   19.25 4999.99   18.49
 5004.59   18.51 5008.19   20.15 5012.09    18.9 5027.39    26.7 5029.29   28.62
 5031.99   31.36 5033.38   31.31 5033.49    31.3 5033.59    31.3 5061.59   30.23
 5091.49   29.83 5124.09    29.9 5183.39   28.62 5243.29   27.81    5247    42.7
    5262    45.5    5282    46.8  5294.2      47
BR D #Mann= 5
 3404.00     0.2    3404     0.1 4967.99    0.04 5031.99     0.2  5294.2     0.2
BR D Banks=4967.99,5031.99

Type RM Length L Ch R = 1 ,5924.1,94,94,94
XS GIS Cut Line= 6
      3158556.45     13849848.30      3158685.04     13848644.41
      3158708.91     13848259.89      3158713.21     13848151.01
      3158714.21     13848104.03      3158604.35     13848020.13
BEGIN DESCRIPTION:
Upstream Section of Bridge/Culvert/Weir
END DESCRIPTION:
#Sta/Elev= 30
    3404   33.16    3519   29.95    3759   30.96    3849   30.69    3999   31.91
    4079   30.34    4169   30.94    4379   29.81  4589.8   29.62    4840   29.09
    4968   31.21  4970.4   26.55  4985.4   23.39  4991.8   20.14    5000   18.49
  5004.6   18.51  5008.2   20.15  5012.1    18.9  5027.4    26.7    5032   31.36
  5061.6   30.23  5124.1    29.9  5127.6   26.29    5212   28.98    5217   30.34
  5228.4   35.92    5237   39.52    5247   42.66    5262   45.55  5294.2      47
#Mann= 5 , 1 , 0
 3404.00     0.2       0  4589.8     0.1       0    4968    0.04       0
    5032     0.1       0  5228.4     0.2       0
#XS Ineff= 2 , 0
       0    4960    30.3    5040       0    30.3
Bank Sta=4968.00,5032.00
Exp/Cntr=0.5,0.3