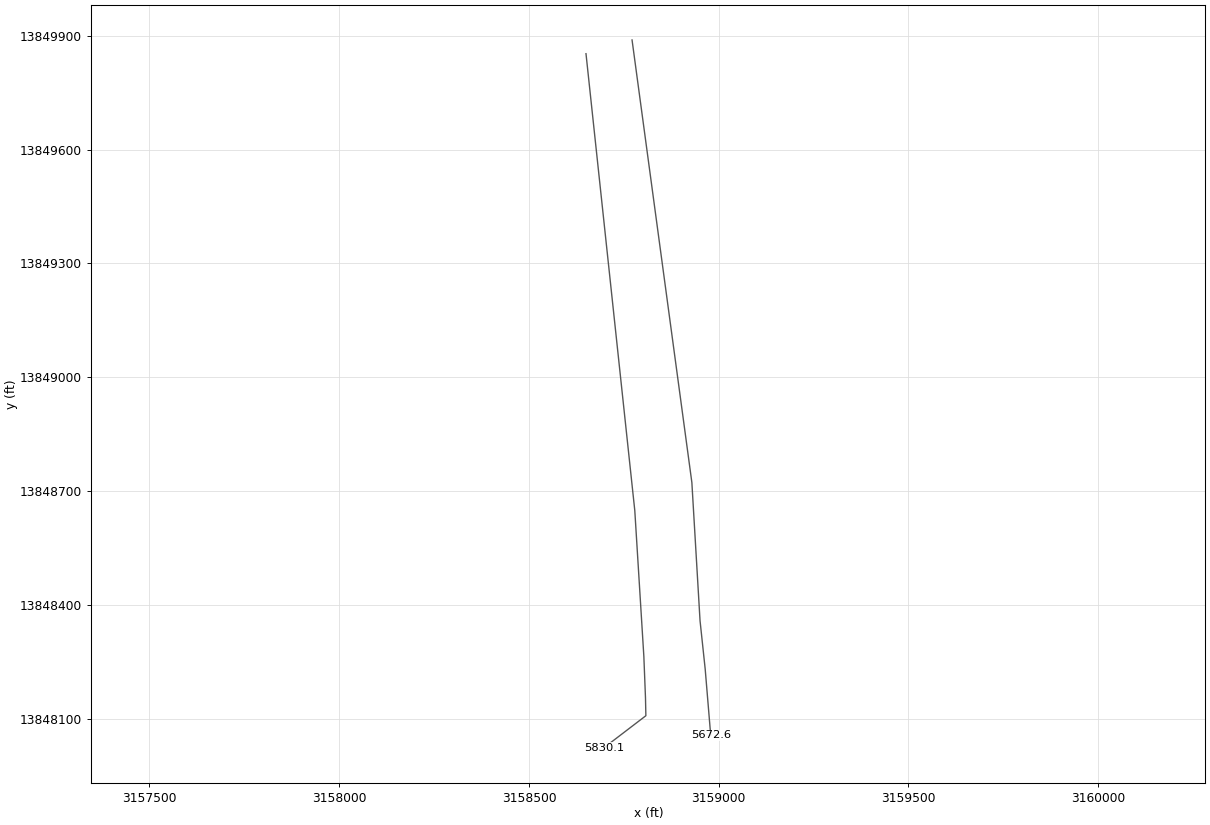
HEC-RAS study H103-00-00.PRJ: H103-00-00

--- H103-00-00.g01 (geometry) --- (continued)

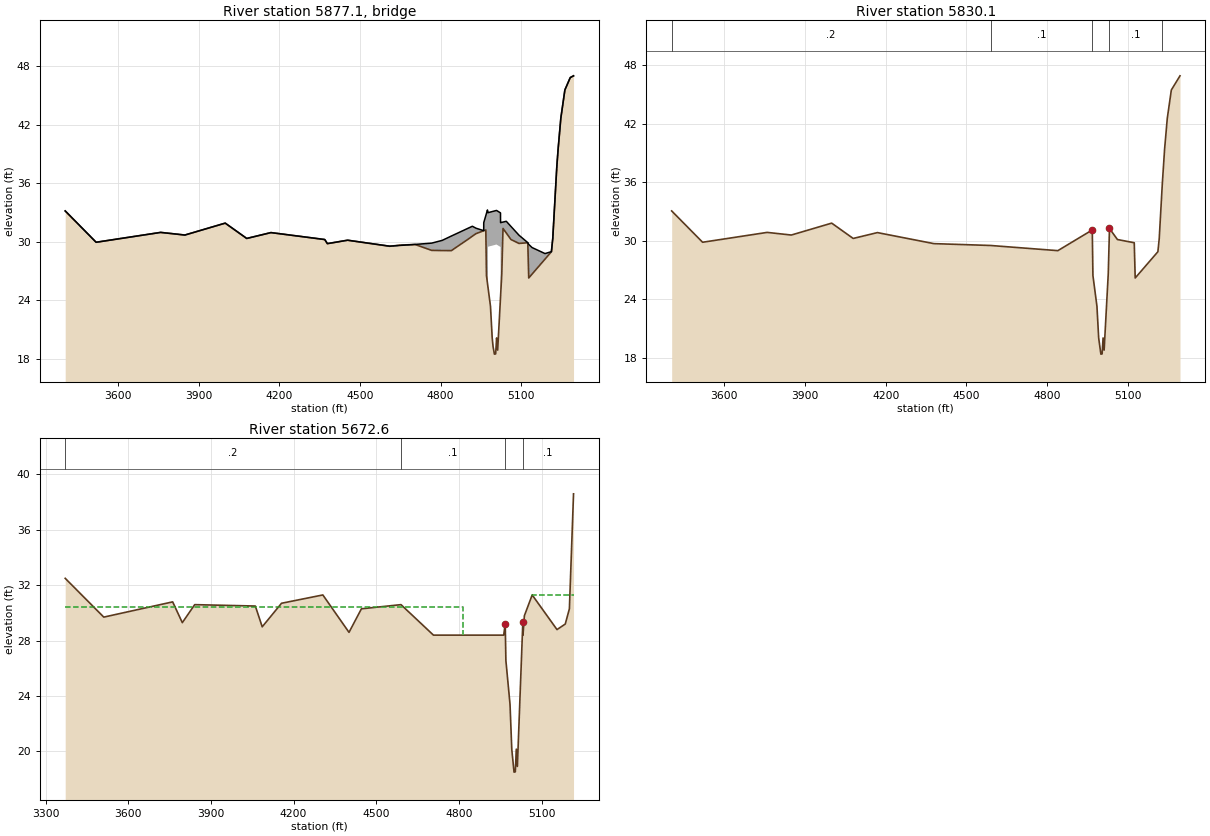
Type RM Length L Ch R = 3 ,5877.1,,,
BEGIN DESCRIPTION:
MERCURY DRIVE
Structure ID: H03-4
END DESCRIPTION:
Bridge Culvert--1,0,-1,-1, 0
Deck Dist Width WeirC Skew NumUp NumDn MinLoCord MaxHiCord MaxSubmerge Is_Ogee
10,74,2.6,, 46, 46,,,0.95,0,1,1,,
    3404    3519    3759    3849    3999    4079    4169    4369    4379    4454
  4610.5  4705.2  4766.4  4805.6    4840    4918  4931.5 4960.19  4960.3    4968
  4970.4  4974.1 4975.91    4976  5007.8 5022.67 5022.78 5022.89    5023  5027.4
    5032  5044.1  5061.6  5091.5  5124.1  5127.6  5139.9  5188.2    5212    5217
    5232    5237    5247    5262    5282  5294.2
   33.16   29.95   30.96   30.69   31.91   30.34   30.94   30.23   29.81   30.16
   29.55   29.73   29.86   30.14   30.59   31.59   31.39   31.14   31.96   32.68
   32.91   33.26   32.98   32.98   33.21   32.96   31.96   31.96   31.96   31.99
   32.02    32.1   31.57   30.67   29.91   29.73   29.41   28.79   28.99   30.35
   37.69   39.53   42.67   45.55   46.82      47
   33.16   29.95   30.96   30.69   31.91   30.34   30.94   30.23   29.81   30.16
   29.54   29.72   29.12    29.1   29.09   30.57   30.83   31.13   31.13   31.21
   26.55   25.77   25.39   29.49   29.72   29.47   29.47   29.47   24.46    26.7
   31.36    30.9   30.23   29.83    29.9   26.29   26.68   28.22   28.98   30.34
   37.68   39.52   42.66   45.55   46.82      47
    3404    3519    3759    3849    3999    4079    4169    4369    4379    4454
  4610.5  4705.2  4766.4  4805.6    4840    4918  4931.5 4960.19  4960.3    4968
  4970.4  4974.1 4975.91    4976  5007.8 5022.67 5022.78 5022.89    5023  5027.4
    5032  5044.1  5061.6  5091.5  5124.1  5127.6  5139.9  5188.2    5212    5217
    5232    5237    5247    5262    5282  5294.2
   33.16   29.95   30.96   30.69   31.91   30.34   30.94   30.23   29.81   30.16
   29.55   29.73   29.86   30.14   30.59   31.59   31.39   31.14   31.96   32.68
   32.91   33.26   32.98   32.98   33.21   32.96   31.96   31.96   31.96   31.99
   32.02    32.1   31.57   30.67   29.91   29.73   29.41   28.79   28.99   30.35
   37.69   39.53   42.67   45.55   46.82      47
   33.06   29.85   30.86   30.59   31.81   30.24   30.84   30.13   29.71   30.06
   29.44   29.62   29.02      29   28.99   30.47   30.73   31.03   31.03   31.11
   26.45   25.67   25.29   29.39   29.62   29.37   29.37   29.37   24.36    26.6
   31.26    30.8   30.13   29.73    29.8   26.19   26.58   28.12   28.88   30.24
   37.58   39.42   42.56   45.45   46.72    46.9
BR Coef= 1 , 1 , 0 ,1.25, 0 ,,,0.8,0,2,0,
Wspro=,,,, 1 ,,,, 0 ,,,, 0 ,,,,-1 ,-1 ,-1 , 0 , 0 , 0 , 0 , 0
BC Design=,, 0 ,, 0 ,,,,,,
BR U #Sta/Elev= 68
    3404   33.16    3519   29.95    3759   30.96    3849   30.69    3999   31.91
    4079   30.34    4169   30.94    4369   30.23    4379   29.81    4454   30.16
  4589.8   29.62  4610.5   29.54  4640.9   29.63    4649   29.66  4705.2   29.72
  4766.4   29.12  4805.6    29.1    4840   29.09  4859.5   29.46  4900.6   30.23
    4918   30.57  4931.5   30.83 4960.19   31.13  4960.3   31.13 4960.41   31.13
    4968   31.21  4970.4   26.55  4974.1   25.77  4975.8   25.41 4975.91   25.39
    4976   25.37  4976.1   25.35  4985.4   23.39  4991.8   20.14  4995.1   19.25
    5000   18.49  5004.6   18.51  5007.8   19.97  5008.2   20.15  5012.1    18.9
  5022.5    24.2 5022.56   24.23 5022.67   24.29 5022.78   24.34 5022.89    24.4
    5023   24.46  5027.4    26.7    5032   31.36  5044.1    30.9  5061.6   30.23
    5089   29.86  5091.5   29.83  5124.1    29.9  5127.6   26.29  5139.9   26.68
  5188.2   28.22    5212   28.98    5217   30.34  5228.4   35.92    5232   37.68
    5237   39.52  5246.3   42.44    5247   42.66    5250   43.24  5261.4   45.43
    5262   45.55    5282   46.82  5294.2      47
BR U #Mann= 5
 3404.00     0.2  4589.8     0.1    4968    0.04    5032     0.1  5228.4     0.2
BR U Banks=4968.00,5032.00
BR D #Sta/Elev= 68
    3404   33.06    3519   29.85    3759   30.86    3849   30.59    3999   31.81
    4079   30.24    4169   30.84    4369   30.13    4379   29.71    4454   30.06
  4589.8   29.52  4610.5   29.44  4640.9   29.53    4649   29.56  4705.2   29.62
  4766.4   29.02  4805.6      29    4840   28.99  4859.5   29.36  4900.6   30.13
    4918   30.47  4931.5   30.73 4960.19   31.03  4960.3   31.03 4960.41   31.03
    4968   31.11  4970.4   26.45  4974.1   25.67  4975.8   25.31 4975.91   25.29
    4976   25.27  4976.1   25.25  4985.4   23.29  4991.8   20.04  4995.1   19.15
    5000   18.39  5004.6   18.41  5007.8   19.87  5008.2   20.05  5012.1    18.8
  5022.5    24.1 5022.56   24.13 5022.67   24.19 5022.78   24.24 5022.89    24.3
    5023   24.36  5027.4    26.6    5032   31.26  5044.1    30.8  5061.6   30.13
    5089   29.76  5091.5   29.73  5124.1    29.8  5127.6   26.19  5139.9   26.58
  5188.2   28.12    5212   28.88    5217   30.24  5228.4   35.82    5232   37.58
    5237   39.42  5246.3   42.34    5247   42.56    5250   43.14  5261.4   45.33
    5262   45.45    5282   46.72  5294.2    46.9
BR D #Mann= 5
 3404.00     0.2  4589.8     0.1    4968    0.04    5032     0.1  5228.4     0.2
BR D Banks=4968.00,5032.00

Type RM Length L Ch R = 1 ,5830.1,157.5,157.5,157.5
XS GIS Cut Line= 6
      3158650.35     13849852.72      3158778.94     13848648.83
      3158802.81     13848264.31      3158807.11     13848155.43
      3158808.11     13848108.45      3158698.24     13848024.54
BEGIN DESCRIPTION:
Downstream Section of Bridge/Culvert/Weir
END DESCRIPTION:
#Sta/Elev= 30
    3404   33.07    3519   29.86    3759   30.87    3849    30.6    3999   31.82
    4079   30.25    4169   30.85    4379   29.72  4589.8   29.53    4840      29
    4968   31.12  4970.4   26.46  4985.4    23.3  4991.8   20.05    5000    18.4
  5004.6   18.42  5008.2   20.06  5012.1   18.81  5027.4   26.61    5032   31.27
  5061.6   30.14  5124.1   29.81  5127.6    26.2    5212   28.89    5217   30.25
  5228.4   35.83    5237   39.43    5247   42.57    5262   45.46  5294.2   46.91
#Mann= 5 , 1 , 0
 3404.00     0.2       0  4589.8     0.1       0    4968    0.04       0
    5032     0.1       0  5228.4     0.2       0
#XS Ineff= 2 , 0
       0    4960    30.3    5040       0    30.3
Bank Sta=4968.00,5032.00
Exp/Cntr=0.5,0.3

Type RM Length L Ch R = 1 ,5672.6,700.6,700.6,706.5
XS GIS Cut Line= 5
      3158771.70     13849888.87      3158929.28     13848723.02
      3158950.84     13848358.73      3158964.44     13848230.97
      3158978.96     13848056.64
BEGIN DESCRIPTION:
Cross Section 5672.6 - Interpolated
END DESCRIPTION:
#Sta/Elev= 30
  3371.1    32.5  3511.1    29.7  3761.1    30.8  3796.1    29.3  3841.1    30.6
  4061.1    30.5  4086.1      29  4156.1    30.7  4306.1    31.3  4401.1    28.6
  4446.1    30.3  4589.8    30.6  4707.5    28.4  4962.5    28.4    4968   29.23
  4970.4   26.57  4985.4   23.41  4991.8   20.16    5000   18.51  5004.6   18.53
  5008.2   20.17  5012.1   18.92    5032   29.38  5032.5    28.4  5037.5    29.8
  5065.9    31.3  5155.9    28.8  5185.9    29.2  5200.9    30.3  5215.9    38.6
#Mann= 4 , 1 , 0
 3371.10     0.2       0  4589.8     0.1       0    4968    0.04       0
    5032     0.1       0
#XS Ineff= 2 , 0
       0    4815    30.4    5065       0    31.3
Bank Sta=4968.00,5032.00
Exp/Cntr=0.3,0.1