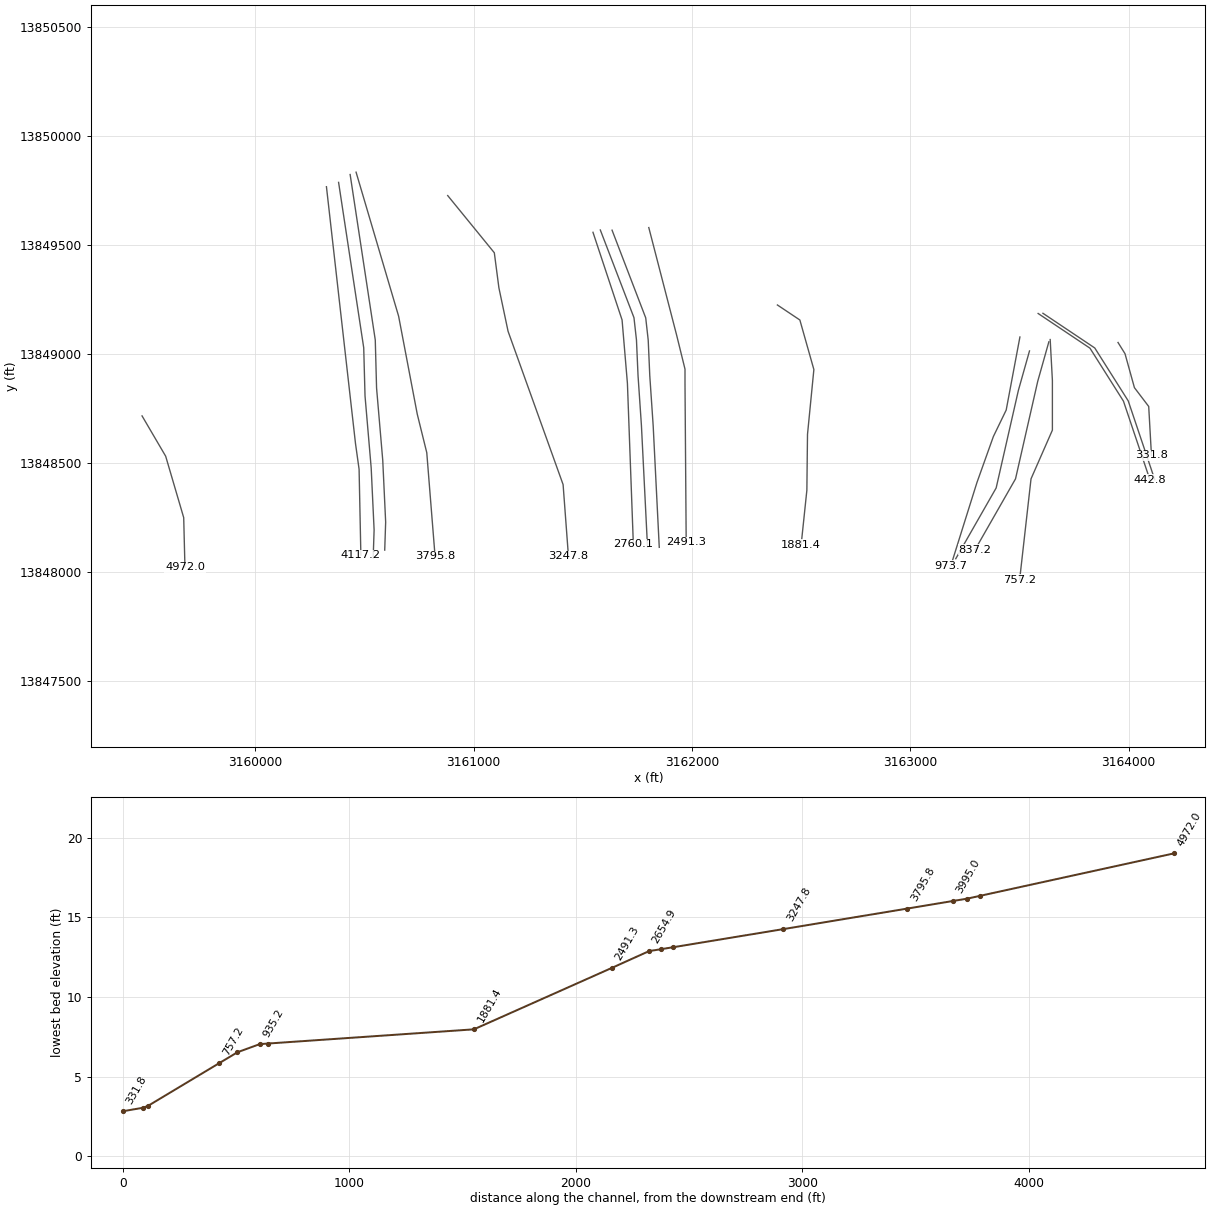
HEC-RAS study H103-00-00.PRJ: H103-00-00

--- H103-00-00.g01 (geometry) --- (continued)

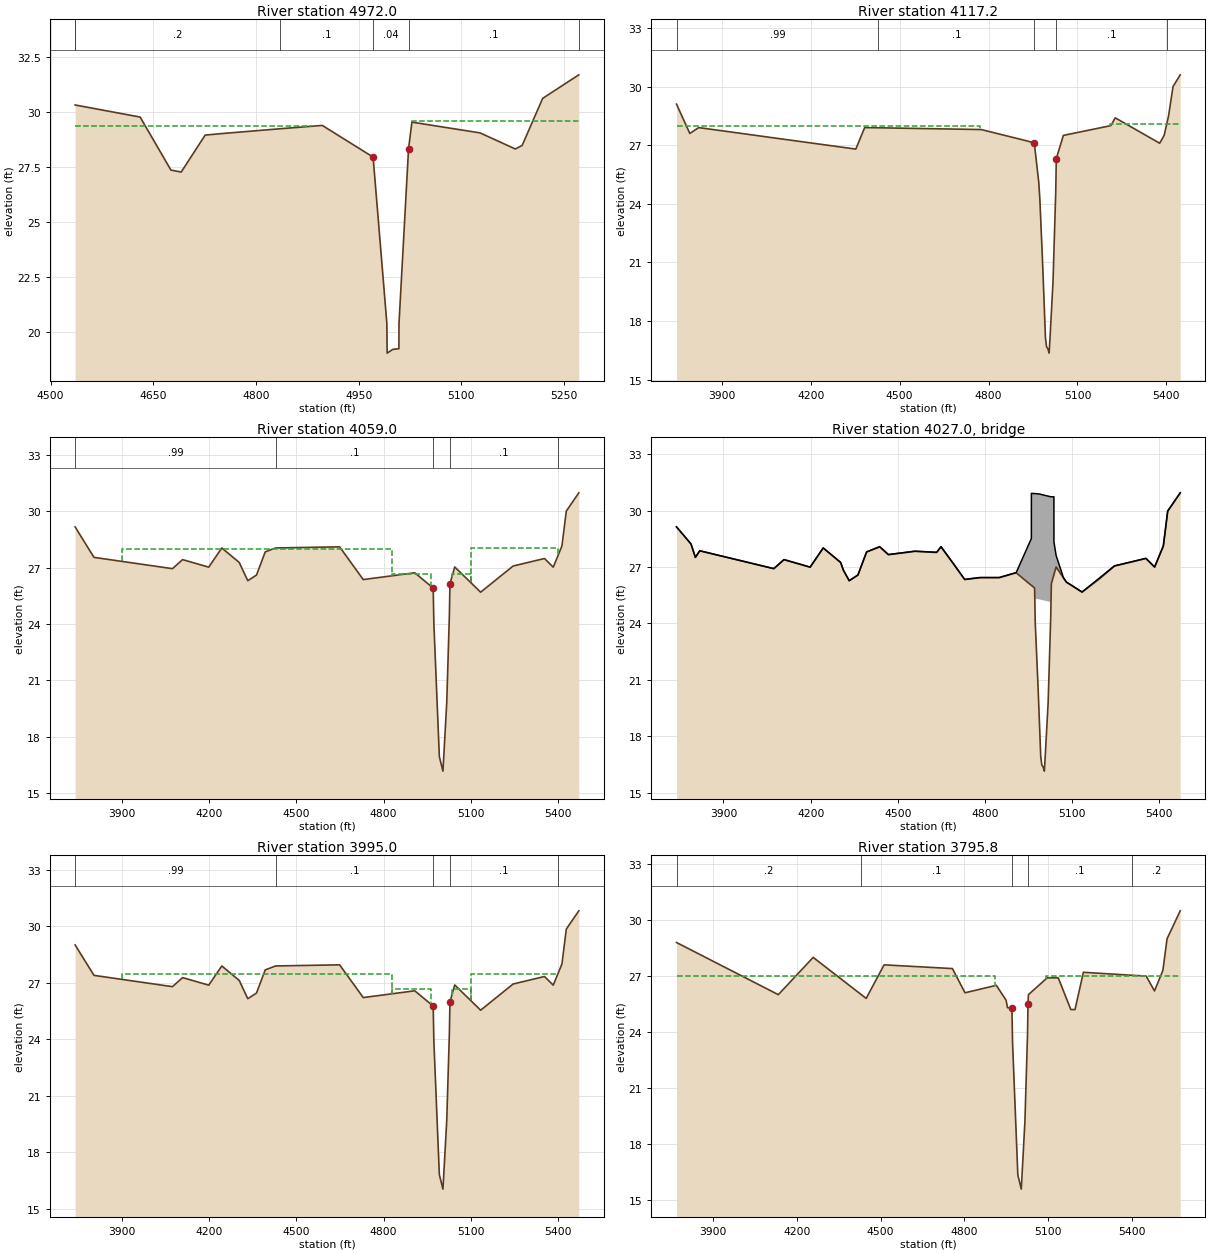
Type RM Length L Ch R = 1 ,4972.0,893.7,854.8,835.9
XS GIS Cut Line= 4
      3159482.04     13848715.06      3159590.22     13848530.03
      3159672.77     13848248.21      3159678.46     13848020.48
BEGIN DESCRIPTION:
Cross Section  4972.0
Located At: NEAR KILROY
END DESCRIPTION:
#Sta/Elev= 21
  4535.7    30.3  4630.7   29.75  4675.7   27.34  4690.7   27.25  4725.7   28.93
    4750      29  4835.7   29.22  4896.8   29.37    4971   27.93  4991.1   20.37
  4991.5   19.02  4999.7   19.19  5008.7   19.22  5008.8   20.36  5022.8   28.32
  5027.7   29.52  5127.3   29.03  5178.7    28.3  5188.7   28.46  5218.7    30.6
  5271.5   31.67
#Mann= 6 , 1 , 0
 4535.70     0.2       0  4535.7     0.2       0  4835.7     0.1       0
    4971    0.04       0  5022.8     0.1       0  5271.5     0.2       0
#XS Ineff= 2 , 0
       0    4880   29.35    5028       0   29.55
Bank Sta=4971.00,5022.80
Exp/Cntr=0.3,0.1

Type RM Length L Ch R = 1 ,4117.2,59.5,58.2,51
XS GIS Cut Line= 5
      3160326.38     13849766.89      3160405.21     13849068.25
      3160459.58     13848587.08      3160475.89     13848470.19
      3160484.05     13848076.02
BEGIN DESCRIPTION:
Cross Section 4117.2 - Interpolated
END DESCRIPTION:
#Sta/Elev= 29
  3747.2    29.1  3792.2    27.6  3822.2    27.9  4352.2    26.8  4382.2    27.9
  4428.5   27.89  4775.3    27.8  4934.5    27.2  4954.5    27.1  4969.5    25.1
  4973.2   24.23  4982.9   20.81  4992.1   17.13  4995.7   16.69  5000.6   16.57
  5004.5   16.36    5008   17.29  5017.5   19.99  5026.8   24.63  5028.6   26.31
  5052.5    27.5  5212.5      28  5227.5    28.4  5377.5    27.1  5392.5    27.5
    5402   28.13  5407.5    28.5  5422.5      30  5446.8    30.6
#Mann= 5 , 1 , 0
 3747.20    0.99       0  4428.5     0.1       0  4954.5    0.04       0
  5028.6     0.1       0    5402     0.2       0
#XS Ineff= 2 , 0
       0    4770      28    5210       0    28.1
Bank Sta=4954.50,5028.60
Exp/Cntr=0.5,0.3

Type RM Length L Ch R = 1 ,4059.0,64,64,64
XS GIS Cut Line= 6
      3160382.03     13849786.70      3160497.10     13849027.68
      3160503.07     13848806.72      3160531.30     13848476.06
      3160544.68     13848191.64      3160540.37     13848063.14
BEGIN DESCRIPTION:
Upstream Section of Bridge/Culvert/Weir
END DESCRIPTION:
#Sta/Elev= 30
  3738.3   29.16  3803.3   27.54  4073.3   26.94  4108.3   27.42  4198.3   27.02
  4243.3   28.04  4303.3   27.27  4332.7    26.3  4362.7    26.6  4392.7   27.83
  4428.5   28.04  4648.8    28.1  4730.2   26.36  4907.5   26.72  4970.9   25.91
  4973.2   24.05  4992.1   16.95  5004.5   16.18  5017.5   19.81  5026.6   24.45
  5028.6   26.13    5045   27.03  5134.3   25.69    5246   27.08  5354.1   27.48
  5384.1   27.02    5402   27.69  5414.1   28.15  5429.1      30  5472.2   30.97
#Mann= 5 , 1 , 0
 3738.30    0.99       0  4428.5     0.1       0  4970.9    0.04       0
  5028.6     0.1       0    5402     0.2       0
#XS Ineff= 4 ,-1
    3900    4830      28  4830.1    4965   26.65    5035  5099.9   26.65
    5100    5400   28.05
Permanent Ineff=
       F       F       F       F
Bank Sta=4970.90,5028.60
Exp/Cntr=0.5,0.3

Type RM Length L Ch R = 3 ,4027.0,,,
BEGIN DESCRIPTION:
WESTSHIRE DRIVE
Structure ID: H03-3
END DESCRIPTION:
Bridge Culvert--1,0,-1,-1, 0
Deck Dist Width WeirC Skew NumUp NumDn MinLoCord MaxHiCord MaxSubmerge Is_Ogee
10,44,2.6,, 42, 42,,,0.95,0,1,1,,
  3738.3  3788.3  3803.3  3818.3  4073.3  4108.3  4198.3  4243.3  4303.3  4312.7
  4332.7  4362.7  4392.7  4437.7  4467.7  4558.8  4633.8  4648.8  4730.2  4783.3
  4849.2  4907.5 4959.77 4959.88  4970.9  4973.1  4986.5 5026.79  5026.9  5028.6
  5037.4 5037.51    5045  5070.2  5080.4  5134.3    5246  5354.1  5384.1  5414.1
  5429.1  5472.2
   29.13   28.22   27.51   27.86   26.91   27.39   26.99   28.01   27.24   26.83
   26.27   26.57    27.8   28.08   27.66   27.84   27.78   28.08   26.34   26.44
   26.44    26.7   28.51   30.91    30.9    30.9   30.88   30.73   30.73   30.73
   30.73   28.33   27.61   26.43    26.2   25.67   27.06   27.46      27   28.12
   29.97   30.94
   29.13   28.22   27.51   27.86   26.91   27.39   26.99   28.01   27.24   26.83
   26.27   26.57    27.8   28.07   27.65   27.83   27.77   28.07   26.33   26.43
   26.43   26.69   26.02   26.02   25.88    25.3   25.28   25.13   24.67    26.1
   26.58   26.59      27   26.42   26.19   25.66   27.05   27.45   26.99   28.12
   29.97   30.94
  3738.3  3788.3  3803.3  3818.3  4073.3  4108.3  4198.3  4243.3  4303.3  4312.7
  4332.7  4362.7  4392.7  4437.7  4467.7  4558.8  4633.8  4648.8  4730.2  4783.3
  4849.2  4907.5 4959.77 4959.88  4970.9  4973.1  4986.5 5026.79  5026.9  5028.6
  5037.4 5037.51    5045  5070.2  5080.4  5134.3    5246  5354.1  5384.1  5414.1
  5429.1  5472.2
   29.13   28.22   27.51   27.86   26.91   27.39   26.99   28.01   27.24   26.83
   26.27   26.57    27.8   28.08   27.66   27.84   27.78   28.08   26.34   26.44
   26.44    26.7   28.51   30.91    30.9    30.9   30.88   30.73   30.73   30.73
   30.73   28.33   27.61   26.43    26.2   25.67   27.06   27.46      27   28.12
   29.97   30.94
   29.03   28.12   27.41   27.76   26.81   27.29   26.89   27.91   27.14   26.73
   26.17   26.47    27.7   27.97   27.55   27.73   27.67   27.97   26.23   26.33
   26.33   26.59   25.92   25.92   25.78    25.2   25.18   25.03   24.57      26
   26.48   26.49    26.9   26.32   26.09   25.56   26.95   27.35   26.89   28.02
   29.87   30.84
Abutment Skew #Up #Dn=, 2 , 2
 4960.00 4973.20
   26.02   24.02
 4960.00 4973.20
   25.92   23.92
BR Coef= 1 , 1 , 0 ,1.25, 0 ,,,0.8,0,2,0,
Wspro=,,,, 1 ,,,, 0 ,,,, 0 ,,,,-1 ,-1 ,-1 , 0 , 0 , 0 , 0 , 0
BC Design=,, 0 ,, 0 ,,,,,,
BR U #Sta/Elev= 71
  3738.3   29.13  3788.3   28.22  3803.3   27.51  3818.3   27.86  4073.3   26.91
  4108.3   27.39  4198.3   26.99  4243.3   28.01  4303.3   27.24  4312.7   26.83
  4332.7   26.27  4362.7   26.57  4392.7    27.8  4428.5   28.01  4437.7   28.07
  4467.7   27.65  4558.8   27.83  4633.8   27.77  4648.8   28.07  4693.8   27.13
    4727    26.4  4729.3   26.35  4730.2   26.33  4783.3   26.43  4785.2   26.43
  4837.1   26.43  4849.2   26.43  4893.3   26.63  4907.5   26.69 4959.77   26.02
 4959.88   26.02 4959.99   26.02 4960.11   26.02  4960.2   26.02  4970.9   25.88
  4973.1    24.1  4973.2   24.02  4982.9    20.6  4986.5   19.16  4992.1   16.92
  4995.7   16.48  5000.6   16.36  5004.5   16.15    5008   17.08  5014.4    18.9
  5017.5   19.78  5026.6   24.42  5026.7    24.5 5026.79   24.58  5026.9   24.67
  5028.6    26.1 5037.29   26.58  5037.4   26.58 5037.51   26.59    5045      27
  5070.2   26.42  5080.4   26.19  5125.4   25.75  5134.3   25.66  5181.7   26.22
    5192   26.34    5236   26.92    5246   27.05  5246.1   27.05  5308.9   27.28
  5354.1   27.45  5384.1   26.99    5402   27.66  5414.1   28.12  5429.1   29.97
  5472.2   30.94
BR U #Mann= 5
 3738.30    0.99  4428.5     0.1  4970.9    0.04  5028.6     0.1    5402     0.2
BR U Banks=4970.90,5028.60
BR D #Sta/Elev= 71
  3738.3   29.03  3788.3   28.12  3803.3   27.41  3818.3   27.76  4073.3   26.81
  4108.3   27.29  4198.3   26.89  4243.3   27.91  4303.3   27.14  4312.7   26.73
  4332.7   26.17  4362.7   26.47  4392.7    27.7  4428.5   27.91  4437.7   27.97
  4467.7   27.55  4558.8   27.73  4633.8   27.67  4648.8   27.97  4693.8   27.03
    4727    26.3  4729.3   26.25  4730.2   26.23  4783.3   26.33  4785.2   26.33
  4837.1   26.33  4849.2   26.33  4893.3   26.53  4907.5   26.59 4959.77   25.92
 4959.88   25.92 4959.99   25.92 4960.11   25.92  4960.2   25.92  4970.9   25.78
  4973.1      24  4973.2   23.92  4982.9    20.5  4986.5   19.06  4992.1   16.82
  4995.7   16.38  5000.6   16.26  5004.5   16.05    5008   16.98  5014.4    18.8
  5017.5   19.68  5026.6   24.32  5026.7    24.4 5026.79   24.48  5026.9   24.57
  5028.6      26 5037.29   26.48  5037.4   26.48 5037.51   26.49    5045    26.9
  5070.2   26.32  5080.4   26.09  5125.4   25.65  5134.3   25.56  5181.7   26.12
    5192   26.24    5236   26.82    5246   26.95  5246.1   26.95  5308.9   27.18
  5354.1   27.35  5384.1   26.89    5402   27.56  5414.1   28.02  5429.1   29.87
  5472.2   30.84
BR D #Mann= 5
 3738.30    0.99  4428.5     0.1  4970.9    0.04  5028.6     0.1    5402     0.2
BR D Banks=4970.90,5028.60

Type RM Length L Ch R = 1 ,3995.0,199.2,199.2,199.2
XS GIS Cut Line= 6
      3160434.91     13849822.75      3160549.98     13849063.72
      3160555.95     13848842.76      3160584.18     13848512.10
      3160597.56     13848227.68      3160593.25     13848099.19
BEGIN DESCRIPTION:
Downstream Section of Bridge/Culvert/Weir
END DESCRIPTION:
#Sta/Elev= 30
  3738.3   29.01  3803.3   27.39  4073.3   26.79  4108.3   27.27  4198.3   26.87
  4243.3   27.89  4303.3   27.12  4332.7   26.15  4362.7   26.45  4392.7   27.68
  4428.5   27.89  4648.8   27.95  4730.2   26.21  4907.5   26.57  4970.9   25.76
  4973.2    23.9  4992.1    16.8  5004.5   16.03  5017.5   19.66  5026.6    24.3
  5028.6   25.98    5045   26.88  5134.3   25.54    5246   26.93  5354.1   27.33
  5384.1   26.87    5402   27.54  5414.1      28  5429.1   29.85  5472.2   30.82
#Mann= 5 , 1 , 0
 3738.30    0.99       0  4428.5     0.1       0  4970.9    0.04       0
  5028.6     0.1       0    5402     0.2       0
#XS Ineff= 4 ,-1
    3900    4830   27.45  4830.1    4965   26.65    5035  5099.9   26.65
    5100    5400   27.45
Permanent Ineff=
       F       F       F       F
Bank Sta=4970.90,5028.60
Exp/Cntr=0.5,0.3

Type RM Length L Ch R = 1 ,3795.8,495.1,548,549.8
XS GIS Cut Line= 5
      3160462.09     13849833.49      3160656.95     13849172.38
      3160742.30     13848723.01      3160785.80     13848546.31
      3160823.86     13848070.58
BEGIN DESCRIPTION:
Cross Section 3795.8 - Interpolated
END DESCRIPTION:
#Sta/Elev= 30
  3768.5    28.8  4133.5      26  4258.5      28  4428.5   26.03  4448.5    25.8
  4512.7    27.6  4757.7    27.4  4802.7    26.1  4915.1    26.5  4950.1    25.7
  4955.1    25.3  4970.9   25.29  4973.2   23.43  4992.1   16.33  5004.5   15.56
  5017.5   19.19  5026.8   23.83  5028.6   25.51  5030.1      26  5097.1    26.9
  5137.1    26.9  5182.1    25.2  5197.1    25.2  5227.1    27.2    5402   27.04
  5452.1      27  5482.1    26.2  5512.1    27.3  5527.1      29  5574.3    30.5
#Mann= 5 , 1 , 0
 3768.50     0.2       0  4428.5     0.1       0  4970.9    0.04       0
  5028.6     0.1       0    5402     0.2       0
#XS Ineff= 2 , 0
       0    4911      27    5094       0      27
Bank Sta=4970.90,5028.60
Exp/Cntr=0.3,0.1

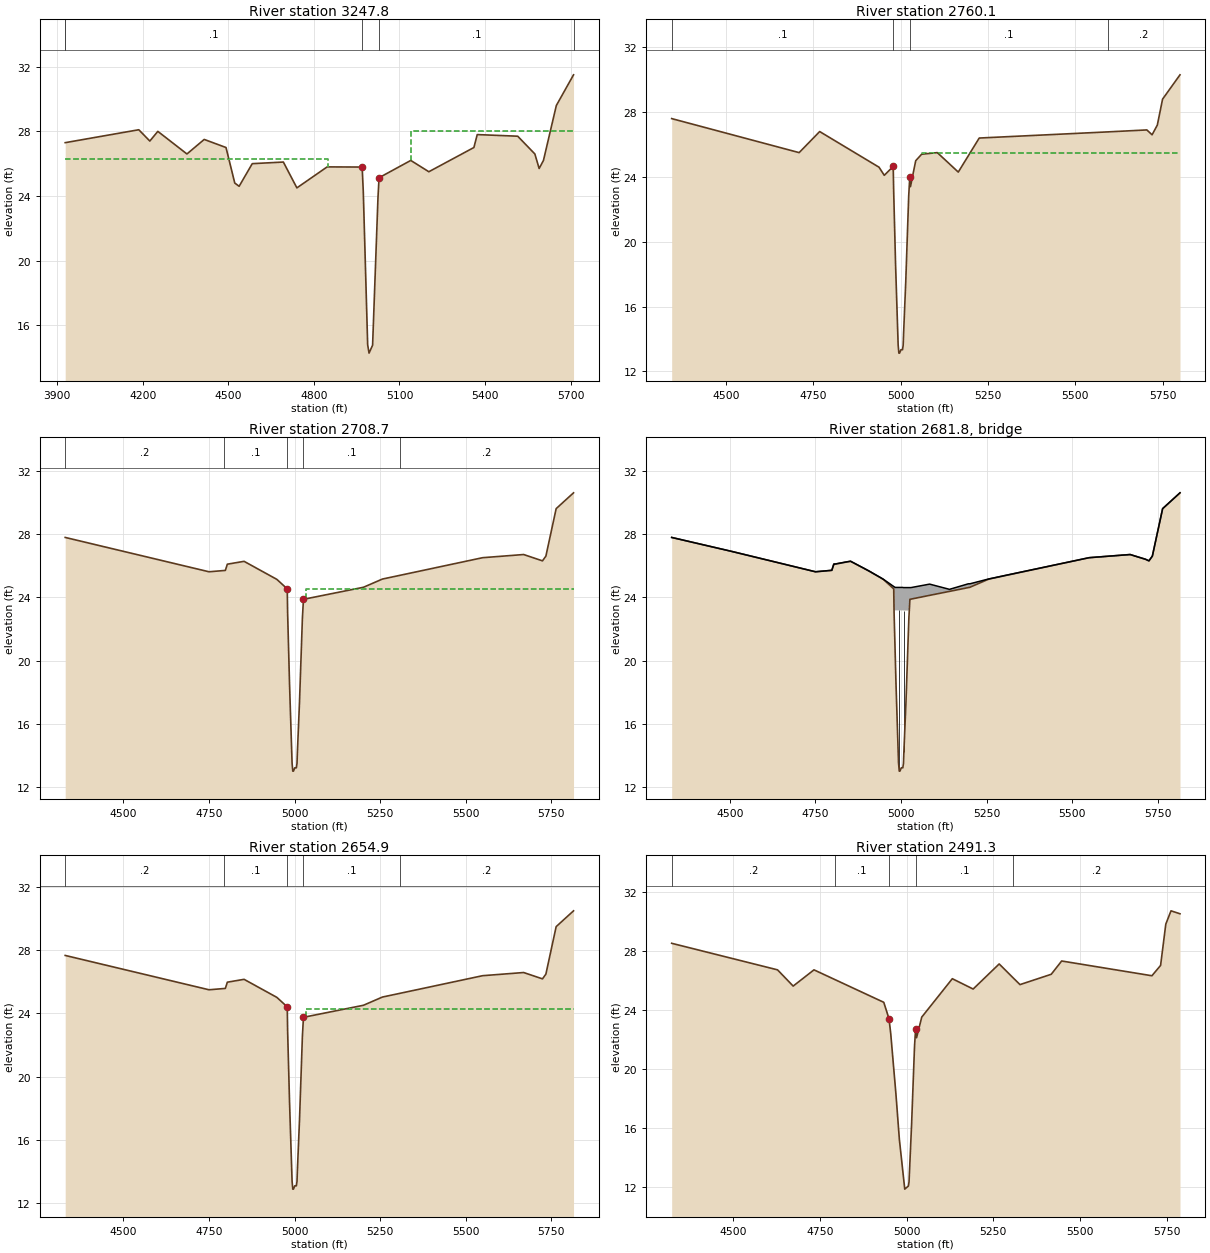
Type RM Length L Ch R = 1 ,3247.8,512.5,487.7,452.2
XS GIS Cut Line= 6
      3160881.67     13849726.16      3161095.14     13849463.71
      3161116.13     13849302.74      3161158.12     13849103.27
      3161410.08     13848399.90      3161434.58     13848070.95
BEGIN DESCRIPTION:
Cross Section 3247.8 - Interpolated
END DESCRIPTION:
#Sta/Elev= 30
  3928.4    27.3  4186.3    28.1    4225    27.4    4253      28  4355.1    26.6
  4415.6    27.5    4492      27  4522.7    24.8    4538    24.6    4584      26
    4693    26.1  4740.4    24.5  4846.5    25.8 4969.16   25.79 4973.12   24.27
 4988.48   14.79 4993.28   14.27 5005.76   14.76 5024.72   23.94 5028.44   25.13
  5139.6    26.2  5202.9    25.5  5360.8      27  5372.5    27.8  5514.3    27.7
  5574.5    26.6  5589.5    25.7  5604.6    26.2  5649.7    29.6    5710    31.5
#Mann= 5 , 1 , 0
 3928.40     0.2       0  3928.4     0.1       0 4969.16    0.04       0
 5028.44     0.1       0    5710     0.2       0
#XS Ineff= 2 , 0
       0    4850    26.3    5140       0      28
Bank Sta=4969.16,5028.44
Exp/Cntr=0.3,0.1

Type RM Length L Ch R = 1 ,2760.1,52,51.4,39.2
XS GIS Cut Line= 4
      3161546.96     13849557.57      3161680.17     13849155.24
      3161704.63     13848864.37      3161731.82     13848124.95
BEGIN DESCRIPTION:
Cross Section 2760.1 - Interpolated
END DESCRIPTION:
#Sta/Elev= 30
  4344.3    27.6  4709.3    25.5  4768.1    26.8  4938.1    24.6  4953.1    24.1
  4978.7   24.65    4980   23.13  4985.4   18.63  4992.8   13.65  4994.9   13.13
  4996.8   13.13  5000.9   13.34  5005.3   13.34  5007.2   13.62  5008.4   14.34
  5014.6   17.54    5023    22.8  5026.1   23.99  5028.1    23.4  5043.1      25
    5060    25.4    5105    25.5    5165    24.3    5225    26.4  5593.9   26.78
    5705    26.9    5720    26.6    5735    27.2    5750    28.8  5799.9    30.3
#Mann= 4 , 1 , 0
 4344.30     0.1       0  4978.7    0.04       0  5026.1     0.1       0
  5593.9     0.2       0
#XS Ineff= 2 , 0
       0                    5060       0    25.5
Bank Sta=4978.70,5026.10
Exp/Cntr=0.5,0.3

Type RM Length L Ch R = 1 ,2708.7,53.8,53.8,53.8
XS GIS Cut Line= 6
      3161580.50     13849568.27      3161734.63     13849165.83
      3161746.05     13849063.58      3161753.22     13848900.57
      3161768.77     13848671.01      3161796.67     13848112.79
BEGIN DESCRIPTION:
Upstream Section of Bridge/Culvert/Weir
END DESCRIPTION:
#Sta/Elev= 29
  4329.6   27.78    4750   25.61  4794.6   25.69  4797.8    25.7  4803.6   26.09
  4852.5   26.27  4948.3   25.13  4978.7   24.53  4979.8   23.01  4985.4   18.51
  4992.8   13.53  4994.9   13.01  4996.8   13.01  5000.9   13.22  5005.3   13.22
  5007.2    13.5  5008.4   14.22  5014.6   17.42    5023   22.68  5026.1   23.87
  5201.4   24.63  5256.9   25.15    5307   25.38  5549.8    26.5  5669.8    26.7
  5724.8    26.3  5734.8    26.6  5764.8    29.6  5815.6    30.6
#Mann= 5 , 1 , 0
 4329.60     0.2       0  4794.6     0.1       0  4978.7    0.04       0
  5026.1     0.1       0    5307     0.2       0
#XS Ineff= 2 , 0
       0    4969    24.6    5033       0    24.5
Bank Sta=4978.70,5026.10
Exp/Cntr=0.5,0.3

Type RM Length L Ch R = 3 ,2681.8,,,
BEGIN DESCRIPTION:
BACA STREET
Structure ID: H03-2
END DESCRIPTION:
Bridge Culvert--1,0,-1,-1, 0
Deck Dist Width WeirC Skew NumUp NumDn MinLoCord MaxHiCord MaxSubmerge Is_Ogee
10,33.8,2.6,,53,53,,,0.95,0,1,1,,
  4329.6  4504.6    4750  4794.6  4797.8  4803.6  4803.7  4804.5  4839.3  4852.5
  4893.6  4905.8  4942.8  4948.3  4978.7 4979.71  4979.8  4979.9    4980 4983.19
  4983.3 4983.41  4985.4  4992.8  4994.9  4996.8  5000.9  5005.3  5007.2  5008.4
  5014.6  5022.9    5023  5026.1 5028.46 5028.57 5028.68 5028.79  5028.9  5083.7
  5141.7  5196.8  5201.4  5256.9  5257.4    5307  5549.8  5669.8  5714.8  5724.8
  5734.8  5764.8  5815.6
   27.78    26.9   25.61    25.7   25.71    26.1   26.09   26.09   26.23   26.28
   25.81   25.67   25.21   25.14   24.68   24.66   24.66   24.66   24.66   24.62
   24.62   24.62   24.62   24.62   24.62   24.62   24.62   24.62   24.61   24.61
   24.61   24.61   24.61   24.61   24.61   24.61   24.61   24.61   24.61   24.83
    24.5   24.85   24.85   25.16   25.16   25.39    26.5    26.7    26.4    26.3
    26.6    29.6    30.6
   27.78    26.9   25.61   25.69    25.7   26.09   26.08   26.08   26.22   26.27
    25.8   25.66    25.2   25.13   24.53   23.13   23.01   23.21   23.21   23.17
   23.17   23.17   23.17   23.17   23.17   23.17   23.17   23.17   23.16   23.16
   23.16   23.16   23.16   23.87   23.88   23.88   23.88   23.88   23.88   24.12
   24.37   24.61   24.63   25.15   25.15   25.38    26.5    26.7    26.4    26.3
    26.6    29.6    30.6
  4329.6  4504.6    4750  4794.6  4797.8  4803.6  4803.7  4804.5  4839.3  4852.5
  4893.6  4905.8  4942.8  4948.3  4978.7 4979.71  4979.8  4979.9    4980 4983.19
  4983.3 4983.41  4985.4  4992.8  4994.9  4996.8  5000.9  5005.3  5007.2  5008.4
  5014.6  5022.9    5023  5026.1 5028.46 5028.57 5028.68 5028.79  5028.9  5083.7
  5141.7  5196.8  5201.4  5256.9  5257.4    5307  5549.8  5669.8  5714.8  5724.8
  5734.8  5764.8  5815.6
   27.78    26.9   25.61    25.7   25.71    26.1   26.09   26.09   26.23   26.28
   25.81   25.67   25.21   25.14   24.68   24.66   24.66   24.66   24.66   24.62
   24.62   24.62   24.62   24.62   24.62   24.62   24.62   24.62   24.61   24.61
   24.61   24.61   24.61   24.61   24.61   24.61   24.61   24.61   24.61   24.83
    24.5   24.85   24.85   25.16   25.16   25.39    26.5    26.7    26.4    26.3
    26.6    29.6    30.6
   27.72   26.84   25.55   25.63   25.64   26.03   26.02   26.02   26.16   26.21
   25.74    25.6   25.14   25.07   24.47   23.07   22.95   23.15   23.15   23.11
   23.11   23.11   23.11   23.11   23.11   23.11   23.11   23.11    23.1    23.1
    23.1    23.1    23.1   23.81   23.82   23.82   23.82   23.82   23.82   24.06
   24.31   24.55   24.57   25.09   25.09   25.32   26.44   26.64   26.34   26.24
   26.54   29.54   30.54
Pier Skew, UpSta & Num, DnSta & Num=,4994.9, 2 ,4994.9, 2 , 0 , 0 , 0 ,,
     0.9     0.9
   12.01   24.17
     0.9     0.9
   11.95   24.11
Pier Skew, UpSta & Num, DnSta & Num=,5008.4, 2 ,5008.4, 2 , 0 , 0 , 0 ,,
     0.9     0.9
   12.95   24.16
     0.9     0.9
   12.89    24.1
Abutment Skew #Up #Dn=, 2 , 2
 5023.00 5028.99
   22.68   23.88
 5023.00 5028.99
   22.62   23.82
BR Coef= 1 , 1 , 0 ,1.25, 0 ,,,0.8,0,2,0,
Wspro=,,,, 1 ,,,, 0 ,,,, 0 ,,,,-1 ,-1 ,-1 , 0 , 0 , 0 , 0 , 0
BC Design=,, 0 ,, 0 ,,,,,,
BR U #Sta/Elev= 53
  4329.6   27.78  4504.6    26.9    4750   25.61  4794.6   25.69  4797.8    25.7
  4803.6   26.09  4803.7   26.08  4804.5   26.08  4839.3   26.22  4852.5   26.27
  4893.6    25.8  4905.8   25.66  4942.8    25.2  4948.3   25.13  4978.7   24.53
 4979.71   23.13  4979.8   23.01  4979.9   22.93    4980   22.85 4983.19   20.29
  4983.3    20.2 4983.41   20.11  4985.4   18.51  4992.8   13.53  4994.9   13.01
  4996.8   13.01  5000.9   13.22  5005.3   13.22  5007.2    13.5  5008.4   14.22
  5014.6   17.42  5022.9   22.62    5023   22.68  5026.1   23.87 5028.46   23.88
 5028.57   23.88 5028.68   23.88 5028.79   23.88  5028.9   23.88  5083.7   24.12
  5141.7   24.37  5196.8   24.61  5201.4   24.63  5256.9   25.15  5257.4   25.15
    5307   25.38  5549.8    26.5  5669.8    26.7  5714.8    26.4  5724.8    26.3
  5734.8    26.6  5764.8    29.6  5815.6    30.6
BR U #Mann= 5
 4329.60     0.2  4794.6     0.1  4978.7    0.04  5026.1     0.1    5307     0.2
BR U Banks=4978.70,5026.10
BR D #Sta/Elev= 53
  4329.6   27.72  4504.6   26.84    4750   25.55  4794.6   25.63  4797.8   25.64
  4803.6   26.03  4803.7   26.02  4804.5   26.02  4839.3   26.16  4852.5   26.21
  4893.6   25.74  4905.8    25.6  4942.8   25.14  4948.3   25.07  4978.7   24.47
 4979.71   23.07  4979.8   22.95  4979.9   22.87    4980   22.79 4983.19   20.23
  4983.3   20.14 4983.41   20.05  4985.4   18.45  4992.8   13.47  4994.9   12.95
  4996.8   12.95  5000.9   13.16  5005.3   13.16  5007.2   13.44  5008.4   14.16
  5014.6   17.36  5022.9   22.56    5023   22.62  5026.1   23.81 5028.46   23.82
 5028.57   23.82 5028.68   23.82 5028.79   23.82  5028.9   23.82  5083.7   24.06
  5141.7   24.31  5196.8   24.55  5201.4   24.57  5256.9   25.09  5257.4   25.09
    5307   25.32  5549.8   26.44  5669.8   26.64  5714.8   26.34  5724.8   26.24
  5734.8   26.54  5764.8   29.54  5815.6   30.54
BR D #Mann= 5
 4329.60     0.2  4794.6     0.1  4978.7    0.04  5026.1     0.1    5307     0.2
BR D Banks=4978.70,5026.10

Type RM Length L Ch R = 1 ,2654.9,163.6,163.6,163.6
XS GIS Cut Line= 6
      3161634.30     13849567.39      3161788.43     13849164.95
      3161799.85     13849062.70      3161807.02     13848899.69
      3161822.57     13848670.13      3161850.46     13848111.91
BEGIN DESCRIPTION:
Downstream Section of Bridge/Culvert/Weir
END DESCRIPTION:
#Sta/Elev= 29
  4329.6   27.66    4750   25.49  4794.6   25.57  4797.8   25.58  4803.6   25.97
  4852.5   26.15  4948.3   25.01  4978.7   24.41  4979.8   22.89  4985.4   18.39
  4992.8   13.41  4994.9   12.89  4996.8   12.89  5000.9    13.1  5005.3    13.1
  5007.2   13.38  5008.4    14.1  5014.6    17.3    5023   22.56  5026.1   23.75
  5201.4   24.51  5256.9   25.03    5307   25.26  5549.8   26.38  5669.8   26.58
  5724.8   26.18  5734.8   26.48  5764.8   29.48  5815.6   30.48
#Mann= 5 , 1 , 0
 4329.60     0.2       0  4794.6     0.1       0  4978.7    0.04       0
  5026.1     0.1       0    5307     0.2       0
#XS Ineff= 2 , 0
       0    4969    24.4    5033       0    24.3
Bank Sta=4978.70,5026.10
Exp/Cntr=0.5,0.3

Type RM Length L Ch R = 1 ,2491.3,656.1,609.9,588.2
XS GIS Cut Line= 5
      3161802.50     13849579.32      3161930.26     13849084.56
      3161968.32     13848929.61      3161968.32     13848861.65
      3161973.76     13848135.82
BEGIN DESCRIPTION:
Cross Section 2491.3 - Interpolated
END DESCRIPTION:
#Sta/Elev= 30
  4323.4    28.5  4628.4    26.7  4673.4    25.6  4733.4    26.7  4794.6   26.03
  4934.4    24.5  4949.4    23.4  4954.4    22.4  4969.4    18.3  4979.4    15.2
  4994.9   11.84  5005.3   12.05  5007.2   12.33  5014.6   16.25    5023   21.51
  5026.1    22.7  5028.9    22.1  5043.9    23.5  5131.9    26.1  5191.9    25.4
  5266.9    27.1    5307   26.16  5326.9    25.7  5416.9    26.4  5446.9    27.3
  5706.9    26.3  5731.9      27  5746.9    29.8  5761.9    30.7  5787.8    30.5
#Mann= 5 , 1 , 0
 4323.40     0.2       0  4794.6     0.1       0  4949.4    0.04       0
  5026.1     0.1       0    5307     0.2       0
Bank Sta=4949.40,5026.10
Exp/Cntr=0.3,0.1

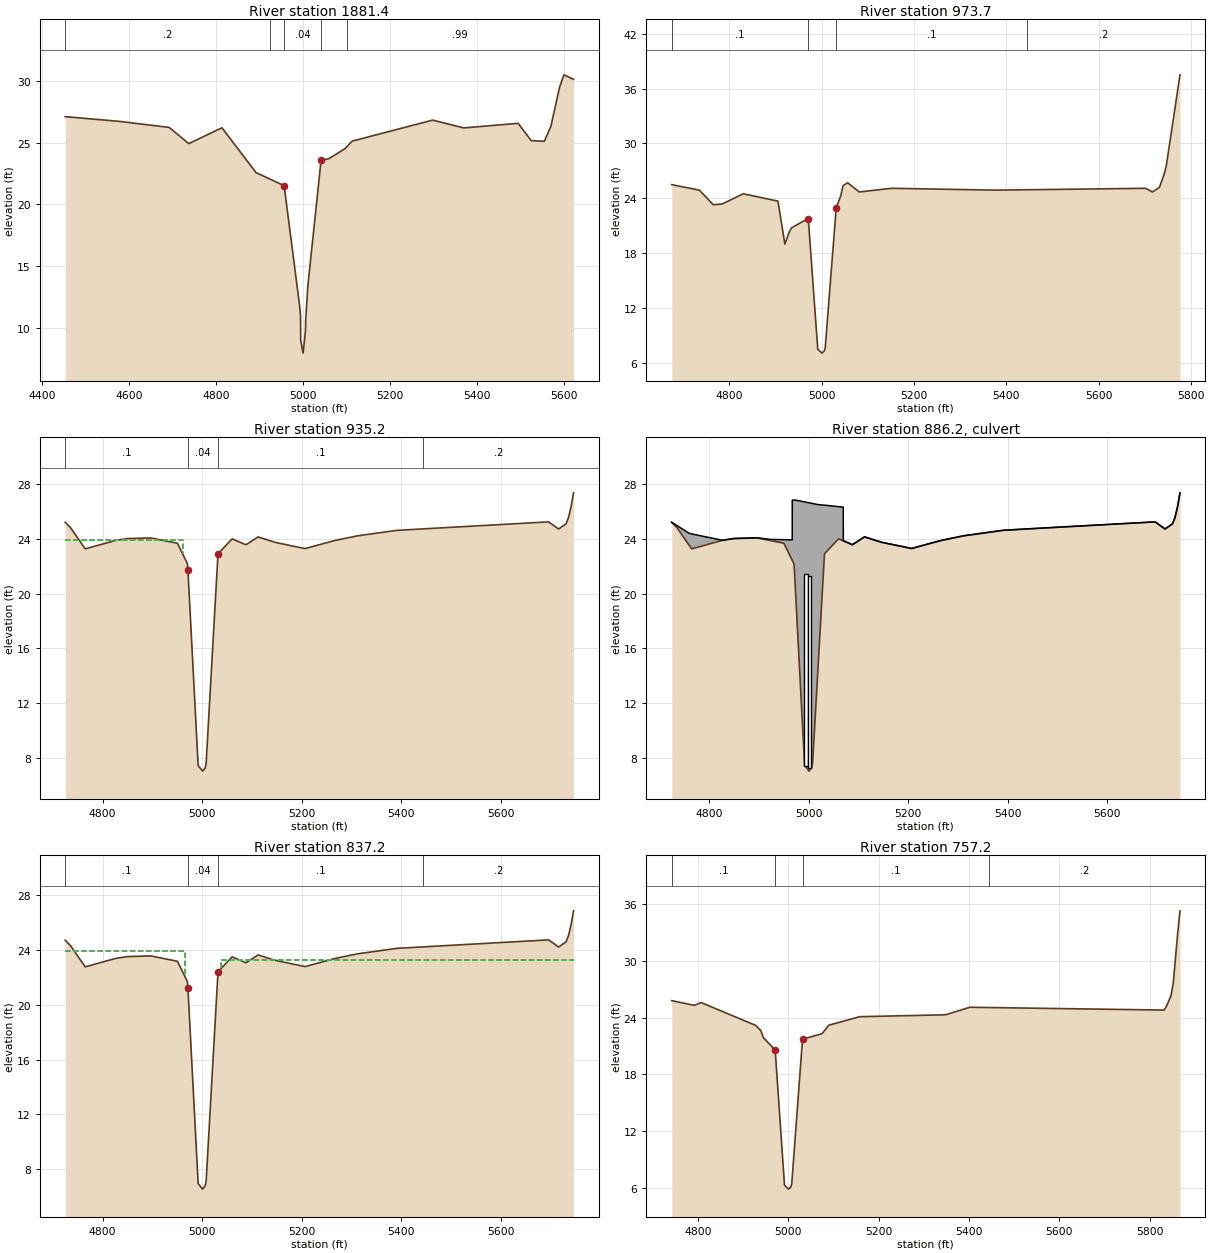
Type RM Length L Ch R = 1 ,1881.4,913.2,907.7,883.8
XS GIS Cut Line= 6
      3162391.43     13849224.09      3162494.29     13849155.19
      3162558.42     13848927.83      3162529.27     13848630.50
      3162526.35     13848373.98      3162500.12     13848123.30
BEGIN DESCRIPTION:
Cross Section  1881.4
Located At: 1ST XS US JOHN RALSTON
END DESCRIPTION:
#Sta/Elev= 29
  4453.7   27.09  4577.5   26.71  4692.5   26.22  4737.5   24.91  4813.7   26.19
  4891.9   22.57  4924.7   22.03  4956.5   21.51  4992.3   11.74  4994.2   10.96
  4994.5    9.02  5000.1    7.98  5005.6    9.85  5005.9   10.63  5010.8   13.35
  5041.3   23.56  5059.1   23.69  5096.5   24.51  5100.1   24.65  5112.5   25.11
  5297.5   26.81    5369   26.18    5494   26.55    5524   25.15    5554    25.1
    5569   26.29    5589   29.46    5599   30.47  5621.1   30.11
#Mann= 5 , 1 , 0
 4453.70     0.2       0  4924.7    0.06       0  4956.5    0.04       0
  5041.3     0.1       0  5100.1    0.99       0
Bank Sta=4956.50,5041.30
Exp/Cntr=0.3,0.1

Type RM Length L Ch R = 1 ,973.7,14.5,38.5,12.4
XS GIS Cut Line= 5
      3163501.93     13849077.09      3163439.09     13848741.91
      3163380.43     13848620.41      3163305.02     13848408.84
      3163185.61     13848027.57
BEGIN DESCRIPTION:
Cross Section 973.7 - Interpolated
END DESCRIPTION:
#Sta/Elev= 29
  4675.7    25.5  4735.7    24.9  4765.7    23.3  4785.7    23.4  4830.7    24.5
  4905.7    23.7  4920.7      19  4930.7    20.4  4935.7    20.8  4971.3    21.8
  4991.9     7.5  4996.4    7.31  5000.9    7.09    5006    7.32    5008    7.69
  5031.8   22.95  5041.7    24.3  5046.7    25.4  5056.7    25.7  5081.7    24.7
  5151.6    25.1  5376.3    24.9  5443.9   24.94  5701.3    25.1  5716.3    24.7
  5731.3    25.2  5741.3    26.6  5746.3    27.6  5775.8    37.5
#Mann= 4 , 1 , 0
 4675.70     0.1       0  4971.3    0.04       0  5031.8     0.1       0
  5443.9     0.2       0
Bank Sta=4971.30,5031.80
Exp/Cntr=0.5,0.3

Type RM Length L Ch R = 1 ,935.2,98,98,98
XS GIS Cut Line= 4
      3163545.82     13849013.19      3163494.97     13848832.37
      3163393.14     13848384.34      3163208.22     13848059.79
BEGIN DESCRIPTION:
Upstream Section of Bridge/Culvert/Weir
END DESCRIPTION:
#Sta/Elev= 29
  4724.9   25.21  4735.1   24.84  4765.1   23.27  4826.5   23.89  4849.8   24.02
  4896.4   24.07  4950.3   23.68  4970.2    22.2  4971.3   21.76  4991.9    7.46
  5000.9    7.05    5006    7.28    5008    7.65  5031.8   22.91  5060.1      24
  5087.9   23.57  5112.2   24.14  5147.1   23.74  5206.6   23.29  5266.4   23.88
  5311.7   24.22  5390.8   24.62  5443.9   24.73  5695.8   25.24  5715.8   24.72
  5730.8    25.1  5735.8   25.56  5740.8   26.33  5745.8   27.36
#Mann= 4 , 1 , 0
 4724.90     0.1       0  4971.3    0.04       0  5031.8     0.1       0
  5443.9     0.2       0
#XS Ineff= 2 , 0
       0  4961.3   23.89  5041.8       0   23.29
Bank Sta=4971.30,5031.80
Exp/Cntr=0.5,0.3

Type RM Length L Ch R = 2 ,886.2,,,
BEGIN DESCRIPTION:
JOHN RALSTON DRIVE
Structure ID: H03-1
END DESCRIPTION:
Bridge Culvert--1,0,-1,-1, 0
Deck Dist Width WeirC Skew NumUp NumDn MinLoCord MaxHiCord MaxSubmerge Is_Ogee
10,78,3,,48,48,,,0.95,0,1,1,,
  4724.9  4735.1  4759.9  4765.1  4826.5  4834.1  4849.8  4869.4  4896.4  4922.9
  4950.3 4966.99  4967.1 4967.21  4967.3  4970.2  4971.3  4972.9  4991.9  4996.4
  5000.9    5006    5008  5019.5  5031.8  5060.1 5069.39  5069.5 5069.61  5073.2
  5087.9  5112.2  5136.4  5147.1  5192.7  5206.6  5250.8  5266.4  5310.1  5311.7
  5390.8  5443.9  5695.8  5715.8  5730.8  5735.8  5740.8  5745.8
    25.2   24.97    24.4   24.35   23.89   23.93   24.02   24.04   24.07   23.95
   23.93   23.92   26.82   26.82   26.82   26.82   26.82   26.82   26.69   26.65
   26.62   26.59   26.57   26.49   26.45   26.34   26.31   26.31   23.85    23.8
   23.57   24.14   23.86   23.74    23.4   23.29   23.73   23.88   24.21   24.22
   24.62   24.73   25.23   24.71   25.09   25.55   26.32   27.35
    25.2   24.83   23.53   23.26   23.88   23.92   24.01   24.03   24.06   23.87
   23.67   22.43   22.42   22.41   22.41   22.19   21.75   20.64    7.45    7.26
    7.04    7.27    7.64   15.01    22.9   23.99   23.85   23.84   23.84   23.79
   23.56   24.13   23.85   23.73   23.39   23.28   23.72   23.87    24.2   24.21
   24.61   24.72   25.23   24.71   25.09   25.55   26.32   27.35
  4724.9  4735.1  4759.9  4765.1  4826.5  4834.1  4849.8  4869.4  4896.4  4922.9
  4950.3 4966.99  4967.1 4967.21  4967.3  4970.2  4971.3  4972.9  4991.9  4996.4
  5000.9    5006    5008  5019.5  5031.8  5060.1 5069.39  5069.5 5069.61  5073.2
  5087.9  5112.2  5136.4  5147.1  5192.7  5206.6  5250.8  5266.4  5310.1  5311.7
  5390.8  5443.9  5695.8  5715.8  5730.8  5735.8  5740.8  5745.8
    25.2   24.97    24.4   24.35   23.89   23.93   24.02   24.04   24.07   23.95
   23.93   23.92   26.82   26.82   26.82   26.82   26.82   26.82   26.69   26.65
   26.62   26.59   26.57   26.49   26.45   26.34   26.31   26.31   23.85    23.8
   23.57   24.14   23.86   23.74    23.4   23.29   23.73   23.88   24.21   24.22
   24.62   24.73   25.23   24.71   25.09   25.55   26.32   27.35
   24.78   24.41   23.11   22.84   23.46    23.5   23.59   23.61   23.64   23.45
   23.25   22.01      22   21.99   21.99   21.77   21.33   20.22    7.03    6.84
    6.62    6.85    7.22   14.59   22.48   23.57   23.43   23.42   23.42   23.37
   23.14   23.71   23.43   23.31   22.97   22.86    23.3   23.45   23.78   23.79
   24.19    24.3   24.81   24.29   24.67   25.13    25.9   26.93
BR Coef= 1 , 0 , 0 ,1.25, 0 ,,,0.8,-1,2,0,
Wspro=,,,, 1 ,,,, 0 ,,,, 0 ,,,,-1 ,-1 ,-1 , 0 , 0 , 0 , 0 , 0
Culvert=2,14.0,7.0,78.0,0.015,0.4,1.0,8,1,7.39,4994.20,7.14,4994.20,Culvert #1  ,0,10
Culvert=2,14.0,7.0,78.0,0.015,0.4,1.0,8,1,7.27,5001.50,7.14,5001.50,Culvert #2  ,0,10
BC Design=,, 0 ,, 0 ,,,,,,
BR U #Sta/Elev= 48
  4724.9    25.2  4735.1   24.83  4759.9   23.53  4765.1   23.26  4826.5   23.88
  4834.1   23.92  4849.8   24.01  4869.4   24.03  4896.4   24.06  4922.9   23.87
  4950.3   23.67 4966.99   22.43  4967.1   22.42 4967.21   22.41  4967.3   22.41
  4970.2   22.19  4971.3   21.75  4972.9   20.64  4991.9    7.45  4996.4    7.26
  5000.9    7.04    5006    7.27    5008    7.64  5019.5   15.01  5031.8    22.9
  5060.1   23.99 5069.39   23.85  5069.5   23.84 5069.61   23.84  5073.2   23.79
  5087.9   23.56  5112.2   24.13  5136.4   23.85  5147.1   23.73  5192.7   23.39
  5206.6   23.28  5250.8   23.72  5266.4   23.87  5310.1    24.2  5311.7   24.21
  5390.8   24.61  5443.9   24.72  5695.8   25.23  5715.8   24.71  5730.8   25.09
  5735.8   25.55  5740.8   26.32  5745.8   27.35
BR U #Mann= 4
 4724.90     0.1  4971.3    0.04  5031.8     0.1  5443.9     0.2
BR U Banks=4971.30,5031.80
BR D #Sta/Elev= 48
  4724.9   24.78  4735.1   24.41  4759.9   23.11  4765.1   22.84  4826.5   23.46
  4834.1    23.5  4849.8   23.59  4869.4   23.61  4896.4   23.64  4922.9   23.45
  4950.3   23.25 4966.99   22.01  4967.1      22 4967.21   21.99  4967.3   21.99
  4970.2   21.77  4971.3   21.33  4972.9   20.22  4991.9    7.03  4996.4    6.84
  5000.9    6.62    5006    6.85    5008    7.22  5019.5   14.59  5031.8   22.48
  5060.1   23.57 5069.39   23.43  5069.5   23.42 5069.61   23.42  5073.2   23.37
  5087.9   23.14  5112.2   23.71  5136.4   23.43  5147.1   23.31  5192.7   22.97
  5206.6   22.86  5250.8    23.3  5266.4   23.45  5310.1   23.78  5311.7   23.79
  5390.8   24.19  5443.9    24.3  5695.8   24.81  5715.8   24.29  5730.8   24.67
  5735.8   25.13  5740.8    25.9  5745.8   26.93
BR D #Mann= 4
 4724.90     0.1  4971.3    0.04  5031.8     0.1  5443.9     0.2
BR D Banks=4971.30,5031.80

Type RM Length L Ch R = 1 ,837.2,80,80,80
XS GIS Cut Line= 4
      3163634.48     13849054.97      3163583.63     13848874.15
      3163481.80     13848426.12      3163296.87     13848101.56
BEGIN DESCRIPTION:
Downstream Section of Bridge/Culvert/Weir
END DESCRIPTION:
#Sta/Elev= 29
  4724.9    24.7  4735.1   24.33  4765.1   22.76  4826.5   23.38  4849.8   23.51
  4896.4   23.56  4950.3   23.17  4970.2   21.69  4971.3   21.25  4991.9    6.95
  5000.9    6.54    5006    6.77    5008    7.14  5031.8    22.4  5060.1   23.49
  5087.9   23.06  5112.2   23.63  5147.1   23.23  5206.6   22.78  5266.4   23.37
  5311.7   23.71  5390.8   24.11  5443.9   24.22  5695.8   24.73  5715.8   24.21
  5730.8   24.59  5735.8   25.05  5740.8   25.82  5745.8   26.85
#Mann= 4 , 1 , 0
 4724.90     0.1       0  4971.3    0.04       0  5031.8     0.1       0
  5443.9     0.2       0
#XS Ineff= 2 , 0
       0 4964.63   23.89 5038.47       0   23.29
Bank Sta=4971.30,5031.80
Exp/Cntr=0.5,0.3

Type RM Length L Ch R = 1 ,757.2,254.7,314.4,349.2
XS GIS Cut Line= 5
      3163640.54     13849065.50      3163650.67     13848878.08
      3163650.67     13848649.74      3163552.81     13848426.24
      3163500.75     13847964.18
BEGIN DESCRIPTION:
Cross Section 757.2 - Interpolated
END DESCRIPTION:
#Sta/Elev= 26
  4742.2    25.8  4792.2    25.3  4807.2    25.6  4927.2    23.2  4929.9    23.1
  4939.9    22.6  4944.9    21.9  4971.3   20.57  4991.9    6.27  4996.4    6.08
  5000.9    5.86    5006    6.09    5008    6.46  5031.8   21.72  5074.9    22.3
  5089.9    23.2  5158.2    24.1  5348.2    24.3  5402.2    25.1  5443.9   25.07
  5832.2    24.8  5837.2    25.2  5847.2    26.3  5852.2    27.6  5862.2      33
  5867.2    35.3
#Mann= 4 , 1 , 0
 4742.20     0.1       0  4971.3    0.04       0  5031.8     0.1       0
  5443.9     0.2       0
Bank Sta=4971.30,5031.80
Exp/Cntr=0.5,0.3

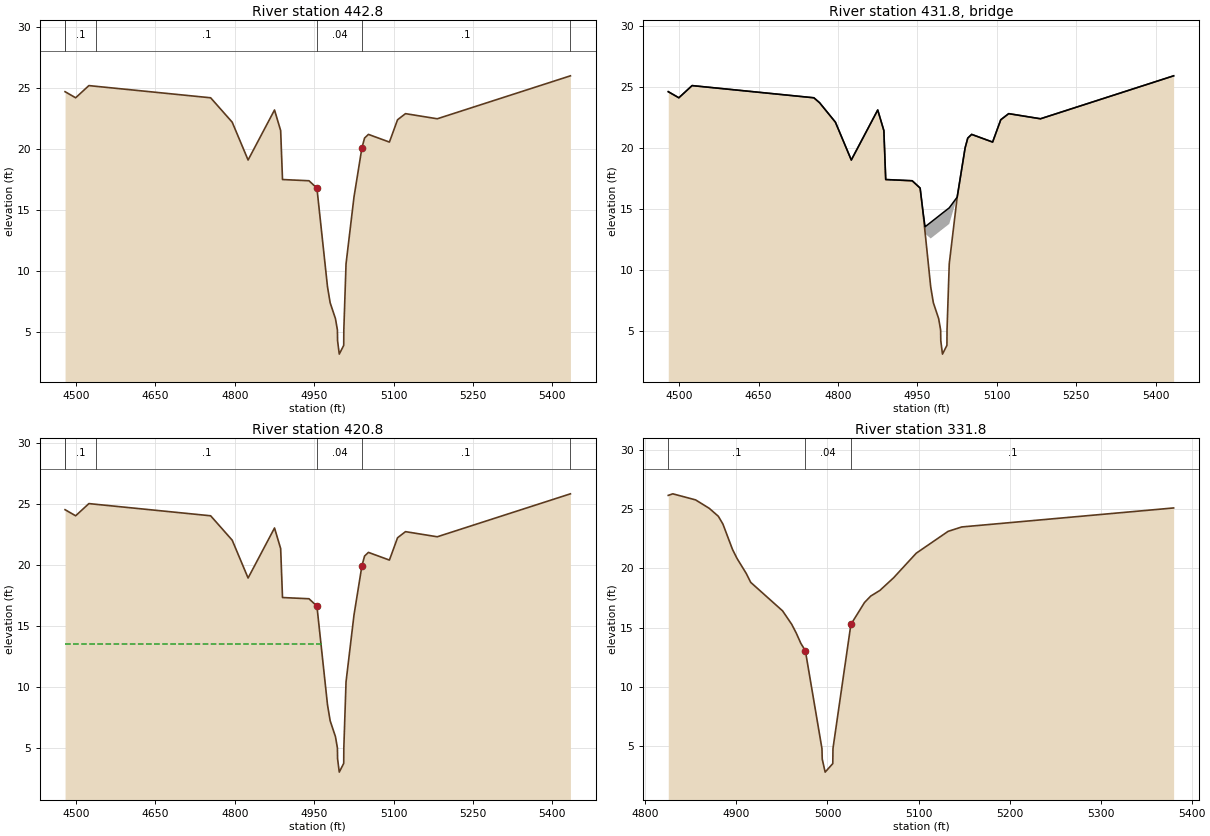
Type RM Length L Ch R = 1 ,442.8,22,22,22
XS GIS Cut Line= 4
      3163585.41     13849185.04      3163822.69     13849025.90
      3163976.03     13848782.88      3164097.54     13848421.23
BEGIN DESCRIPTION:
Upstream Section of Bridge/Culvert/Weir
END DESCRIPTION:
#Sta/Elev= 30
  4479.5   24.69  4499.5   24.19  4524.5   25.19    4538   25.13  4754.5   24.19
  4795.2   22.19  4825.2   19.09 4875.12   23.19 4886.72    21.5  4890.2   17.49
  4940.2   17.39  4955.2   16.79  4975.2    8.69  4980.2    7.39  4990.2    6.09
 4993.92    5.16 4994.22    4.28 4997.42    3.18 5005.82     3.9 5006.02    5.17
  5010.2   10.58  5025.2   16.05  5040.2   20.09  5045.2   20.89  5052.5   21.19
 5092.12   20.56  5107.5   22.39  5122.5   22.89 5182.52   22.47    5434   25.99
#Mann= 6 , 1 , 0
 4479.50     0.2       0  4479.5     0.1       0    4538     0.1       0
  4955.2    0.04       0  5040.2     0.1       0    5434     0.2       0
#XS Ineff= 2 , 0
       0    4963    13.6    5026       0    15.9
Bank Sta=4955.20,5040.20
Exp/Cntr=0.5,0.3

Type RM Length L Ch R = 3 ,431.8,,,
BEGIN DESCRIPTION:
PIPELINE
END DESCRIPTION:
Bridge Culvert--1,0,-1,-1, 0
Deck Dist Width WeirC Skew NumUp NumDn MinLoCord MaxHiCord MaxSubmerge Is_Ogee
10,2,2.6,,38,38,,,0.95,0,1,1,,
  4479.5  4499.5  4524.5    4538  4754.5  4765.2  4795.2  4825.2 4875.12 4886.72
  4890.2  4940.2  4955.2  4960.2 4964.62 4964.73 4964.82  4975.2  4980.2  4990.2
 4993.92 4994.22 4997.42 5005.82 5006.02  5010.2  5025.2 5031.11 5031.22 5031.32
  5040.2  5045.2  5052.5 5092.12  5107.5  5122.5 5182.52    5434
   24.61   24.11   25.11   25.05   24.11   23.71   22.11   19.01   23.11   21.42
   17.41   17.31   16.71   14.91   13.54   13.54   13.55    13.9   14.07   14.41
   14.54   14.55   14.66   14.94   14.95   15.09   15.97   17.56   17.59   17.62
   20.01   20.81   21.11   20.48   22.31   22.81   22.39   25.91
   24.61   24.11   25.11   25.05   24.11   23.71   22.11   19.01   23.11   21.42
   17.41   17.31   16.71   14.91   13.05   13.01   12.97   12.58   12.75   13.09
   13.22   13.23   13.34   13.62   13.63   13.77   15.97   17.56   17.59   17.62
   20.01   20.81   21.11   20.48   22.31   22.81   22.39   25.91
  4479.5  4499.5  4524.5    4538  4754.5  4765.2  4795.2  4825.2 4875.12 4886.72
  4890.2  4940.2  4955.2  4960.2 4964.62 4964.73 4964.82  4975.2  4980.2  4990.2
 4993.92 4994.22 4997.42 5005.82 5006.02  5010.2  5025.2 5031.11 5031.22 5031.32
  5040.2  5045.2  5052.5 5092.12  5107.5  5122.5 5182.52    5434
    24.6    24.1    25.1   25.04    24.1    23.7    22.1      19    23.1   21.41
    17.4    17.3    16.7    14.9   13.54   13.54   13.55    13.9   14.07   14.41
   14.54   14.55   14.66   14.94   14.95   15.09   15.97   17.56   17.59   17.61
      20    20.8    21.1   20.47    22.3    22.8   22.38    25.9
    24.6    24.1    25.1   25.04    24.1    23.7    22.1      19    23.1   21.41
    17.4    17.3    16.7    14.9   13.04      13   12.96   12.57   12.74   13.08
   13.21   13.22   13.33   13.61   13.62   13.76   15.96   17.55   17.58   17.61
      20    20.8    21.1   20.47    22.3    22.8   22.38    25.9
BR Coef= 1 , 1 , 0 ,1.25, 0 ,,,0.8,-1,2,0,
Wspro=,,,, 1 ,,,, 0 ,,,, 0 ,,,,-1 ,-1 ,-1 , 0 , 0 , 0 , 0 , 0
BC Design=,, 0 ,, 0 ,,,,,,
BR U #Sta/Elev= 38
  4479.5   24.61  4499.5   24.11  4524.5   25.11    4538   25.05  4754.5   24.11
  4765.2   23.71  4795.2   22.11  4825.2   19.01 4875.12   23.11 4886.72   21.42
  4890.2   17.41  4940.2   17.31  4955.2   16.71  4960.2   14.91 4964.62   13.05
 4964.73   13.01 4964.82   12.97  4975.2    8.61  4980.2    7.31  4990.2    6.01
 4993.92    5.08 4994.22     4.2 4997.42     3.1 5005.82    3.82 5006.02    5.09
  5010.2    10.5  5025.2   15.97 5031.11   17.56 5031.22   17.59 5031.32   17.62
  5040.2   20.01  5045.2   20.81  5052.5   21.11 5092.12   20.48  5107.5   22.31
  5122.5   22.81 5182.52   22.39    5434   25.91
BR U #Mann= 6
 4479.50     0.2  4479.5     0.1    4538     0.1  4955.2   0.045  5040.2     0.1
    5434     0.2
BR U Banks=4955.20,5040.20
BR D #Sta/Elev= 38
  4479.5    24.6  4499.5    24.1  4524.5    25.1    4538   25.04  4754.5    24.1
  4765.2    23.7  4795.2    22.1  4825.2      19 4875.12    23.1 4886.72   21.41
  4890.2    17.4  4940.2    17.3  4955.2    16.7  4960.2    14.9 4964.62   13.04
 4964.73      13 4964.82   12.96  4975.2     8.6  4980.2     7.3  4990.2       6
 4993.92    5.07 4994.22    4.19 4997.42    3.09 5005.82    3.81 5006.02    5.08
  5010.2   10.49  5025.2   15.96 5031.11   17.55 5031.22   17.58 5031.32   17.61
  5040.2      20  5045.2    20.8  5052.5    21.1 5092.12   20.47  5107.5    22.3
  5122.5    22.8 5182.52   22.38    5434    25.9
BR D #Mann= 6
 4479.50     0.2  4479.5     0.1    4538     0.1  4955.2   0.045  5040.2     0.1
    5434     0.2
BR D Banks=4955.20,5040.20

Type RM Length L Ch R = 1 ,420.8,89,89,89
XS GIS Cut Line= 4
      3163607.39     13849185.96      3163844.67     13849026.82
      3163998.01     13848783.80      3164119.52     13848422.15
BEGIN DESCRIPTION:
Downstream Section of Bridge/Culvert/Weir
END DESCRIPTION:
#Sta/Elev= 30
  4479.5   24.57  4499.5   24.07  4524.5   25.07    4538   25.01  4754.5   24.07
  4795.2   22.07  4825.2   18.97 4875.12   23.07 4886.72   21.38  4890.2   17.37
  4940.2   17.27  4955.2   16.67  4975.2    8.57  4980.2    7.27  4990.2    5.97
 4993.92    5.04 4994.22    4.16 4997.42    3.06 5005.82    3.78 5006.02    5.05
  5010.2   10.46  5025.2   15.93  5040.2   19.97  5045.2   20.77  5052.5   21.07
 5092.12   20.44  5107.5   22.27  5122.5   22.77 5182.52   22.35    5434   25.87
#Mann= 6 , 1 , 0
 4479.50     0.2       0  4479.5     0.1       0    4538     0.1       0
  4955.2    0.04       0  5040.2     0.1       0    5434     0.2       0
#XS Ineff= 2 , 0
       0    4963    13.6    5026       0    15.9
Bank Sta=4955.20,5040.20
Exp/Cntr=0.5,0.3

Type RM Length L Ch R = 1 ,331.8,0,0,0
XS GIS Cut Line= 5
      3163951.18     13849051.99      3163983.19     13849000.50
      3164026.33     13848844.62      3164091.74     13848758.33
      3164104.27     13848534.26
BEGIN DESCRIPTION:
Cross Section 331.8
END DESCRIPTION:
#Sta/Elev= 29
  4825.1   26.15  4830.1   26.28  4855.1   25.77  4870.1   25.06  4880.1   24.39
  4885.1   23.74  4895.7   21.59  4900.7   20.83  4910.7   19.58  4915.7   18.82
  4950.7   16.42  4960.7   15.29  4965.7   14.55  4970.7   13.69  4975.7   13.06
 4993.92    4.82 4994.22    3.94 4997.42    2.84 5005.82    3.56 5006.02    4.83
  5025.7   15.28  5040.7   17.13  5047.5   17.67  5057.5   18.14  5072.5    19.2
  5097.5   21.28  5132.5   23.12  5147.5   23.49  5380.2   25.09
#Mann= 3 , 1 , 0
 4825.10     0.1       0  4975.7    0.04       0  5025.7     0.1       0
Bank Sta=4975.70,5025.70
Exp/Cntr=0.3,0.1

Chan Stop Cuts=-1